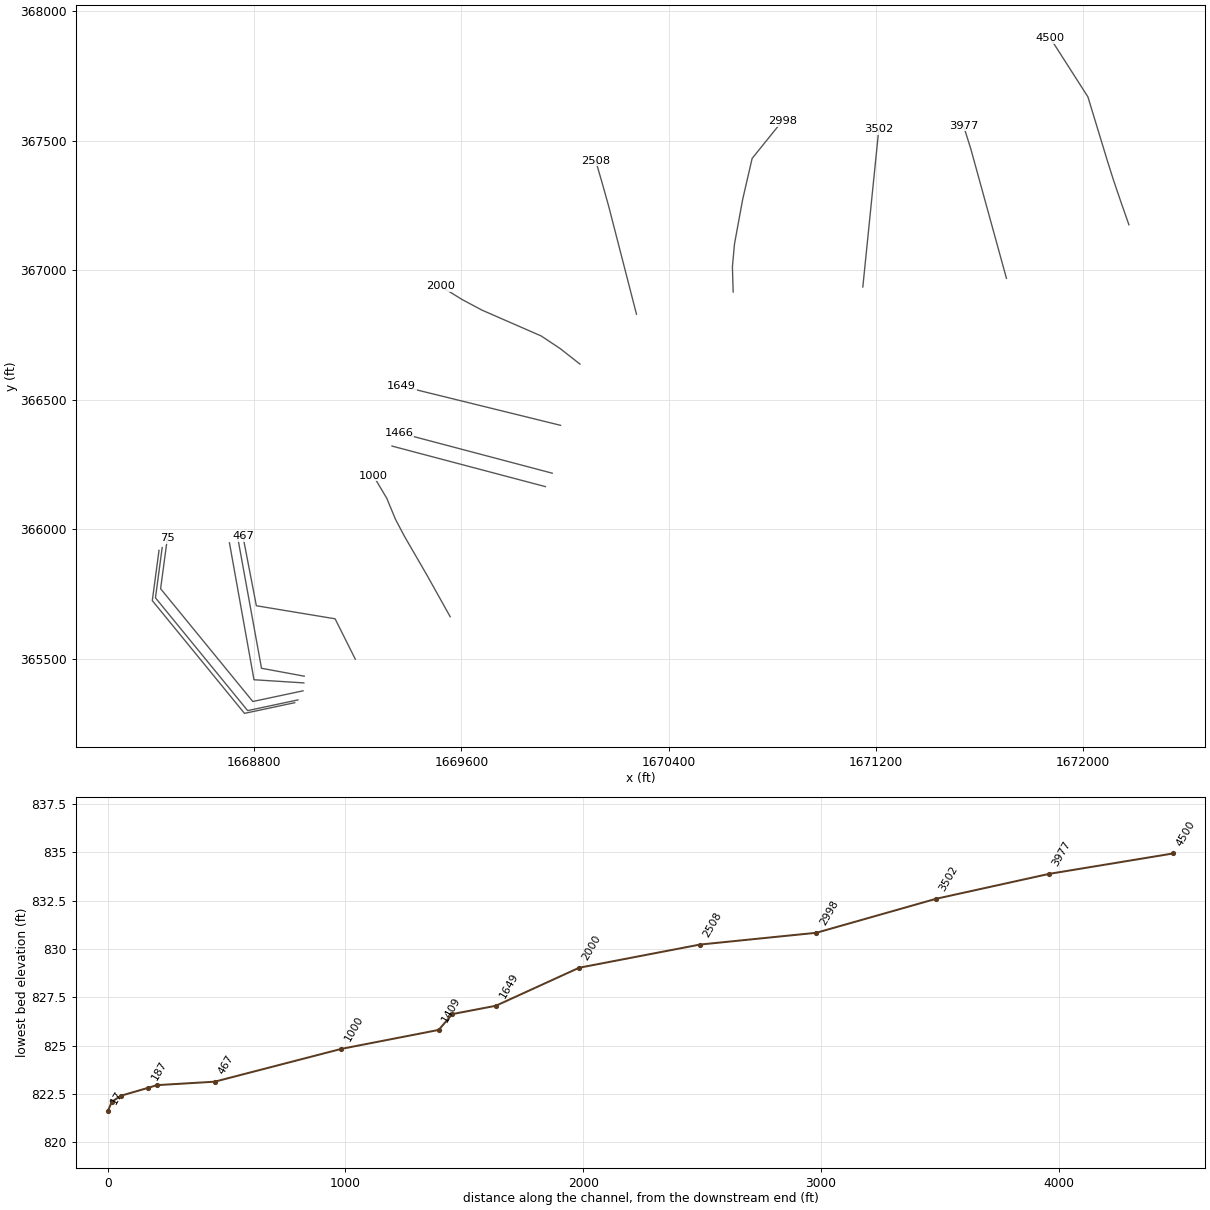
HEC-RAS study PRICERN.prj: PRICERN

--- PRICERN.g01 (geometry) --- (continued)

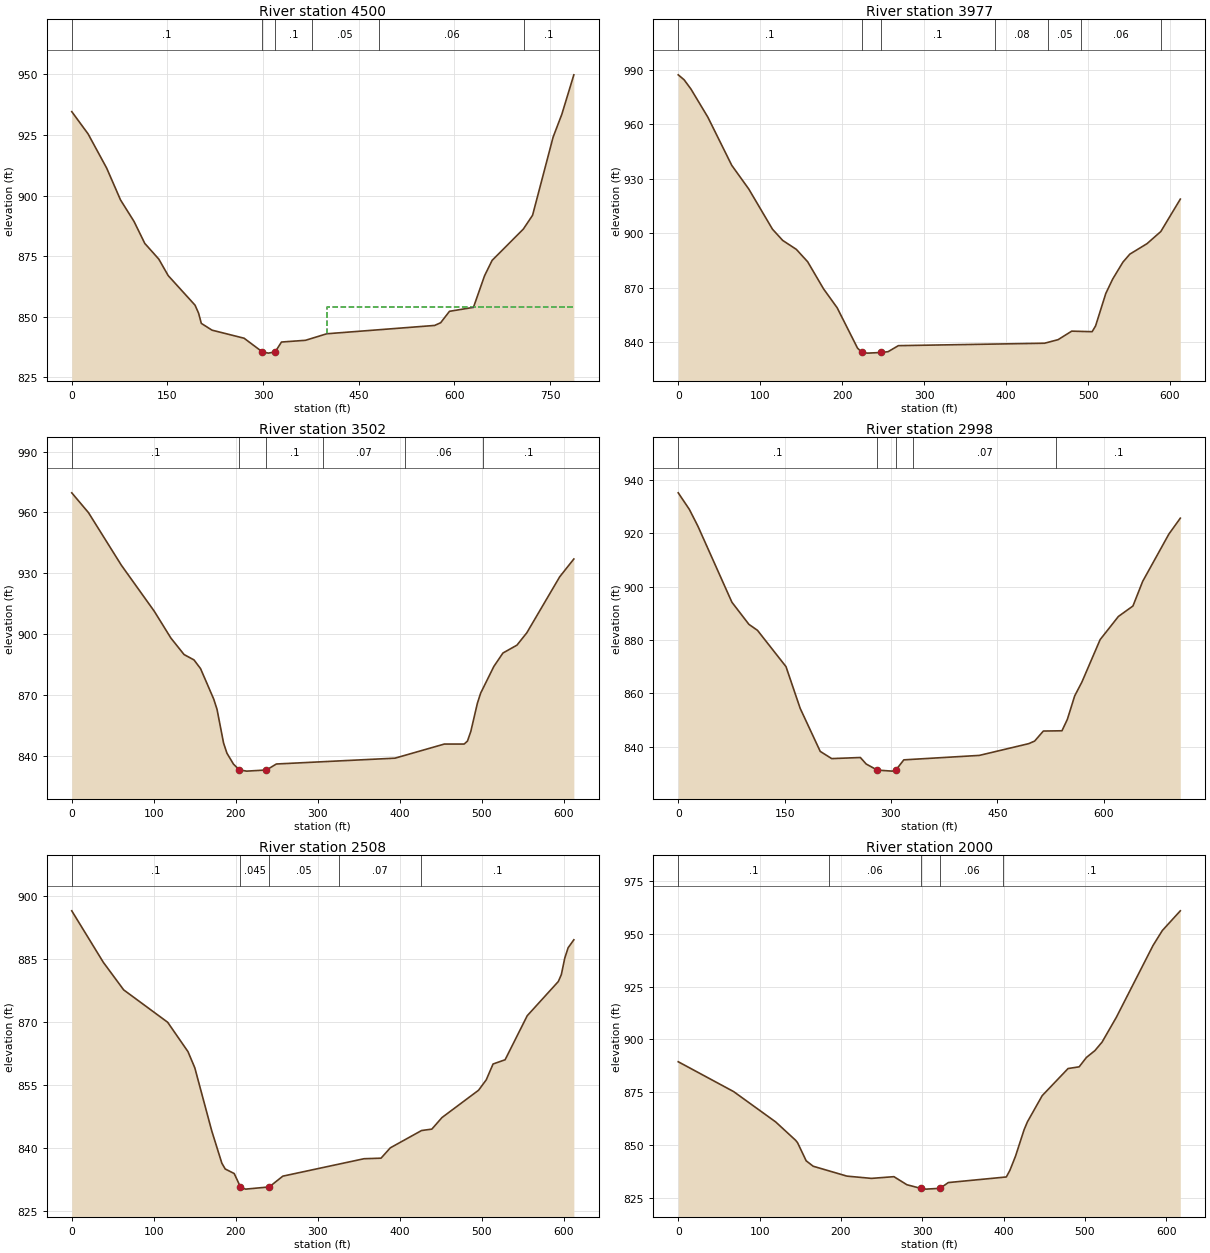
Type RM Length L Ch R = 1 ,4500    ,524.6,523.1,522.9
XS GIS Cut Line= 6
1672177.62926584367176.3778220861672146.62735935367264.938012421
1672118.39874126367347.8095658421672095.71637192367419.302861169
1672019.28673476367670.4296555071671874.61824122 367896.35310729
#Sta/Elev= 30
       0  934.64    25.6  925.45    54.7  911.34    76.5  898.17    97.6  889.32
   114.5  880.24   136.5  873.75   151.2  866.95   193.3  854.74   198.9  851.41
   203.1  847.23   219.9  844.43   270.2   841.1   298.7  835.48   308.3  834.95
   318.9  835.46   328.8  839.53   366.4  840.24   399.8  842.94     569  846.38
   578.4   847.5   592.2  852.21   629.8  853.84   647.2  866.89   659.1  873.26
     708  886.16   722.5  891.87   754.7  924.13   768.4  933.57   787.2  949.84
#Mann= 6 ,-1,0
       0      .1       0   298.7    .045       0   318.9      .1       0
  376.38     .05       0  481.38     .06       0  708.88      .1       0
#XS Ineff= 2 , 0
                             400          853.97
Permanent Ineff=
       F       F
Bank Sta=298.7,318.9
XS Rating Curve= 0 ,0
Exp/Cntr(USF)=0,0
Exp/Cntr=0.3,0.1

Type RM Length L Ch R = 1 ,3977    ,480.4,475.4,470.1
XS GIS Cut Line= 6
1671704.74257597366969.6209423451671636.71384064 367216.67589443
1671610.16566538367313.0877751021671590.25527215367385.396357512
1671567.02565981367469.7564250141671538.78391839367559.219172603
#Sta/Elev= 30
       0  987.22     7.2  984.48    15.5  979.39    36.2  963.84    65.3  937.36
      86  924.35     115  902.16   127.5  895.97   144.1  891.06   157.9  884.24
   177.3   869.3   193.9  858.89   218.8  836.61  224.47  834.25   231.2  833.89
   247.8  834.25   256.1  834.69   268.6  838.01     447  839.34   463.5  841.31
   480.1     846     505   845.7   509.2  848.87   521.7  866.78   530.1  874.71
   542.6  884.03     551  888.42     572  894.21   588.8  900.88   612.6  918.74
#Mann= 7 ,-1,0
       0      .1       0  224.47    .045       0   247.8      .1       0
  386.25     .08       0  451.25     .05       0  491.25     .06       0
  588.75      .1       0
Bank Sta=224.47,247.8
XS Rating Curve= 0 ,0
Exp/Cntr(USF)=0,0
Exp/Cntr=0.3,0.1

Type RM Length L Ch R = 1 ,3502    ,505,503.8,502.5
XS GIS Cut Line= 6
1671150.13415166366936.2461620381671159.58787292367029.520581792
1671175.97399499367191.2046416211671186.02417175367290.698209043
1671202.40799724367452.3579907081671211.86139041367545.628145377
#Sta/Elev= 30
       0  969.65    20.4  959.88    60.6  933.94   100.8  911.25   120.9  898.15
     137  890.01   149.1  887.37   157.1  883.09   173.2  868.05   177.2  863.04
   185.2  846.41   189.3  841.43   197.3  836.04  204.49   833.2   213.4   832.6
   237.5  833.16   249.6  836.11   394.3  838.98   454.6  845.94   478.7  845.94
   482.7  847.39   486.8  852.13   494.8  865.98   498.8     871   514.9  884.14
     526  890.76   543.1  894.64   555.1  900.71   595.3  928.33612.5003  937.07
#Mann= 6 ,-1,0
       0      .1       0  204.49    .045       0   237.5      .1       0
  306.26     .07       0  406.26     .06       0  501.26      .1       0
Bank Sta=204.49,237.5
XS Rating Curve= 0 ,0
Exp/Cntr(USF)=0,0
Exp/Cntr=0.3,0.1

Type RM Length L Ch R = 1 ,2998    ,483.1,489.4,493.4
XS GIS Cut Line= 6
1670649.47418568366916.843907847   1670646.54637367013.917860686
1670654.51584226367101.8894695181670686.10108092367274.199820428
1670722.64037792367432.5387426011670838.79167603367576.516389852
#Sta/Elev= 30
       0  935.26    15.7  929.04    27.7  922.77    75.7  894.22    99.7  885.91
   111.8  883.66     152  870.05     172   854.4   200.3  838.24   216.5  835.54
   256.9  835.95   265.1  833.51   280.8  831.22   301.8  830.84   306.8  831.19
   318.2  835.07   424.7  836.74   494.4  841.15   502.7  842.11     515  845.88
   541.3  845.98   548.9  850.29   559.2  859.06   569.4  864.27   595.1  880.18
   620.9  888.88   641.4   892.8   655.1  902.03   692.1  919.79   708.2  925.75
#Mann= 5 ,-1,0
       0      .1       0   280.8    .045       0   306.8      .1       0
  330.65     .07       0  533.18      .1       0
Bank Sta=280.8,306.8
XS Rating Curve= 0 ,0
Exp/Cntr(USF)=0,0
Exp/Cntr=0.3,0.1

Type RM Length L Ch R = 1 ,2508    ,497.5,508.4,521.6
XS GIS Cut Line= 6
1670276.10523497 366831.206544271670252.72109539366921.993436192
1670187.24419222367176.1960117711670168.53622438367248.825459693
1670144.91619288367333.0976008521670118.83061514367423.188299944
#Sta/Elev= 30
       0  896.51    38.5  884.25    63.3  877.69     117  869.97   141.8  862.97
   150.1  859.13   170.7  844.16   183.1  836.41   187.2  835.03   198.2  833.94
  205.81  830.74     212  830.23   240.9  830.75   257.5  833.32   356.6  837.47
   377.3   837.6   388.7  840.07   426.8  844.19   439.3  844.52   451.7  847.28
   496.3  853.78   505.7  856.26     514  860.03   528.7  861.04   555.7  871.53
   593.6  879.67   597.3  881.32   601.5  885.26   605.6  887.72 612.561  889.61
#Mann= 5 ,-1,0
       0      .1       0  205.81    .045       0   240.9     .05       0
  326.25     .07       0  426.25      .1       0
Bank Sta=205.81,240.9
XS Rating Curve= 0 ,0
Exp/Cntr(USF)=0,0
Exp/Cntr=0.3,0.1

Type RM Length L Ch R = 1 ,2000    ,348.5,350.5,352
XS GIS Cut Line= 6
1670057.80312492366638.4993046671669982.28785601366697.760341004
1669908.35854192366746.9626704161669679.22776659366846.958205342
1669601.81880067366888.3554322571669521.38490643 366938.12436159
#Sta/Elev= 30
       0  889.38    68.1  875.24   119.8  860.86   144.3  852.17   146.7  851.01
   157.3  842.43   165.9  839.87   207.4  835.19   237.5  834.12   265.1  834.93
   281.1  831.11   298.5  829.35   304.6  829.03   321.8  829.41     332  832.14
   403.3  834.79   407.7  837.94   414.6  844.65   425.1  857.12   429.2  860.89
   447.4  873.32   479.2  886.16   492.8  886.97   501.8  891.43   512.2  894.67
     521  898.69   538.5  910.41   583.7  944.51   595.1  951.56617.1669  960.88
#Mann= 5 ,-1,0
       0      .1       0   184.8     .06       0   298.5    .045       0
   321.8     .06       0   399.8      .1       0
Bank Sta=298.5,321.8
XS Rating Curve= 0 ,0
Exp/Cntr(USF)=0,0
Exp/Cntr=0.3,0.1

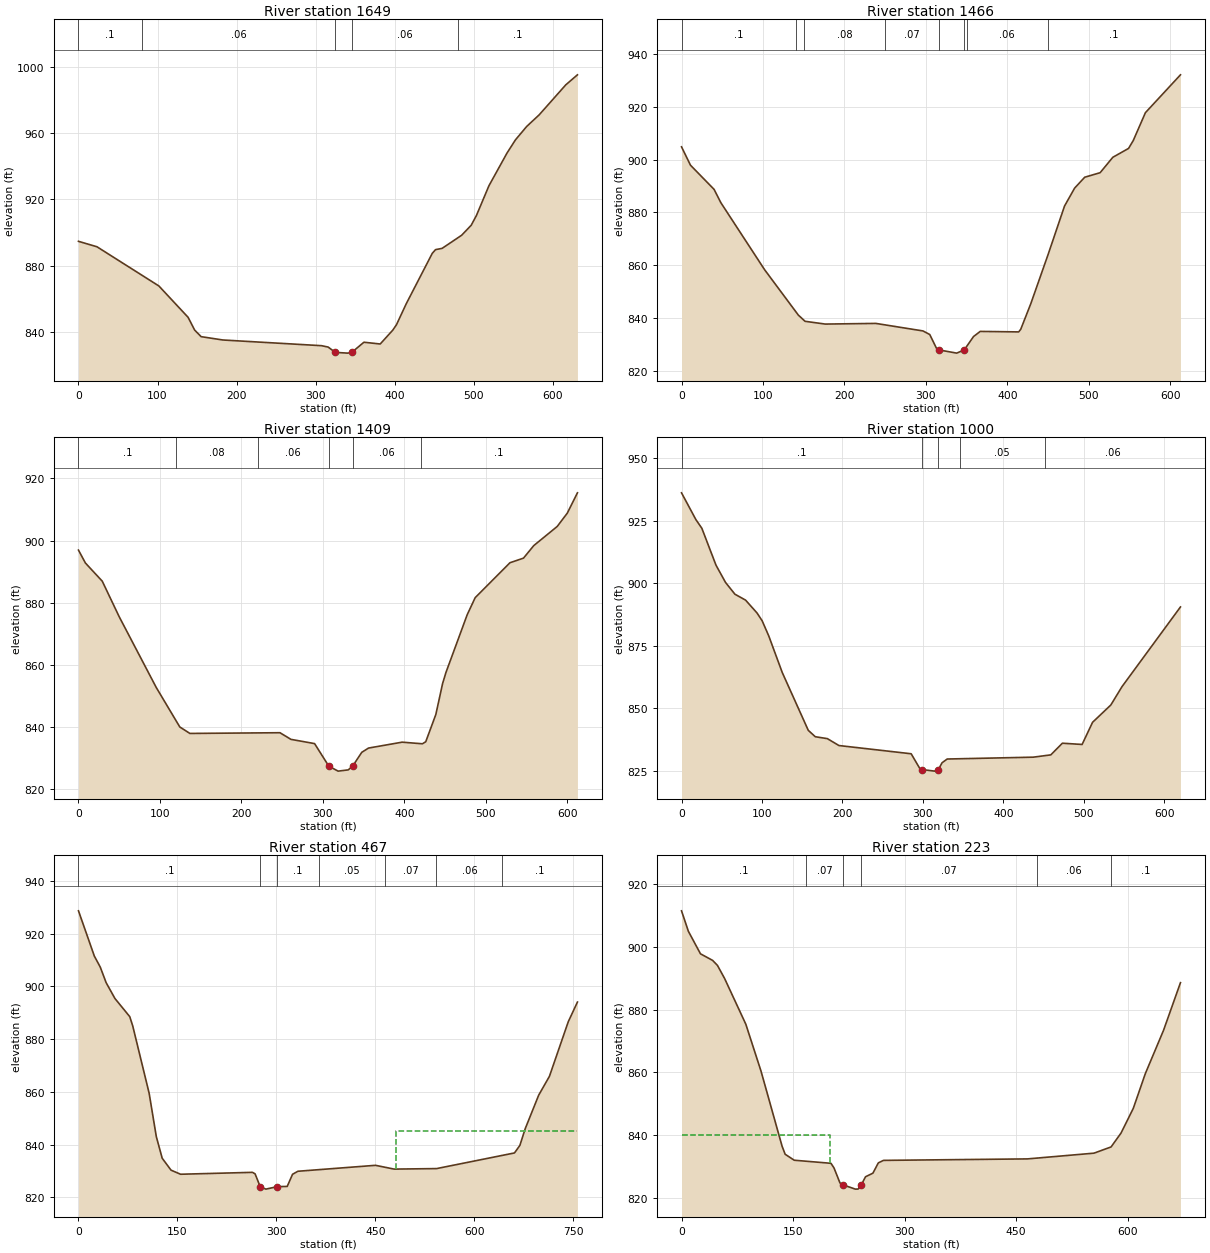
Type RM Length L Ch R = 1 ,1649    ,183.2,183,181.6
XS GIS Cut Line= 2
1669982.83347858366402.0480398591669369.77457927366552.954845843
#Sta/Elev= 30
       0  894.69    23.4  891.39   101.7   867.7   138.7  848.72     147  841.01
   155.2  837.02   182.8     835   307.6  831.56   315.9  830.73     325  827.51
   340.6  827.06  345.83  827.53   361.2  833.65   381.8  832.58   397.7  840.96
   402.4  844.26   414.7  856.89   447.7  887.44   451.8  889.66   460.1  890.43
   484.8  898.34   496.9  904.39   503.5  910.26   519.4  928.33   542.4  948.21
     553  956.11   567.2  964.19   582.8  971.12   616.6  989.33631.3589   995.4
#Mann= 5 ,-1,0
       0      .1       0      80     .06       0     325    .045       0
  345.83     .06       0     480      .1       0
Bank Sta=325,345.83
XS Rating Curve= 0 ,0
Exp/Cntr(USF)=0,0
Exp/Cntr=0.3,0.1

Type RM Length L Ch R = 1 ,1466    ,57.3,57.3,57.2
XS GIS Cut Line= 2
1669950.76578231366217.1872025281669358.45656882366373.753013736
#Sta/Elev= 30
       0  904.81      11  897.85      40  888.68    48.3  883.64     102  858.25
   143.4  841.06   151.7  838.69   176.5  837.64   238.6  837.89   296.5  835.04
   304.8  833.68     313  828.51   315.8  827.86   337.9  826.63  347.19  827.86
   358.6  832.93   366.8  834.86     414  834.67   416.5  835.64   428.9  845.38
     450  863.89   470.3  882.37   482.7  889.16   495.1  893.29     514     895
   529.6  900.84   548.9   904.2   554.7  907.19   569.6  917.74612.6525  932.09
#Mann= 8 ,-1,0
       0      .1       0     140     .07       0     150     .08       0
     250     .07       0   315.8    .045       0  347.19     .07       0
     350     .06       0     450      .1       0
Bank Sta=315.8,347.19
XS Rating Curve= 0 ,0
Exp/Cntr(USF)=0,0
Exp/Cntr=0.3,0.1

Type RM Length L Ch R = 1 ,1409    ,413.9,409.1,394.6
XS GIS Cut Line= 2
1669924.35709126 366165.312987971669332.04787777366321.878799179
#Sta/Elev= 30
       0  896.94     8.5  892.79    29.2  886.94    49.9  875.55    95.4  852.77
   124.4  840.02   136.8  837.94   247.4  838.17   260.9  836.03   289.9  834.67
  307.36  827.41   318.8  825.81   331.2  826.21  336.63  827.41   347.8  831.85
   356.1  833.23   397.4  835.13   422.3  834.61   426.4  835.27   438.8  844.05
   447.1  854.01   451.2  857.56   477.3  876.15   487.1  881.64   529.8  892.88
   546.4  894.36   559.1  898.41   587.8  904.55   600.2  908.84612.6525  915.38
#Mann= 6 ,-1,0
       0      .1       0     120     .08       0     220     .06       0
  307.36    .045       0  336.63     .06       0     420      .1       0
Bank Sta=307.36,336.63
XS Rating Curve= 0 ,0
Exp/Cntr(USF)=0,0
Exp/Cntr=0.3,0.1

Type RM Length L Ch R = 1 ,1000    ,524,533.2,545.8
XS GIS Cut Line= 6
1669556.79330017365662.8844580051669468.35810959365821.119705841
1669380.67783876365972.5695341681669345.58342075366038.913889676
1669311.91714951366120.1532285061669260.35130775366207.019524589
#Sta/Elev= 30
       0  936.08    17.9  925.36    25.3  921.89    42.9  907.14    54.7  900.27
    66.4  895.55    79.6   893.2    93.8  888.08   100.3   884.9   108.5  878.84
   125.2  864.28   157.6  841.13   166.3  838.58   181.3  837.82   195.7  835.06
   285.5  831.77   296.1  825.96  299.41  825.44   314.6  824.83   319.3  825.44
   323.9  828.17   330.3  829.67   437.4  830.41   459.1  831.33   473.5  835.99
     498  835.49     511  844.34   533.7  851.26   547.6   858.6620.2841  890.46
#Mann= 5 ,-1,0
       0      .1       0  299.41    .045       0   319.3      .1       0
  346.27     .05       0  451.33     .06       0
Bank Sta=299.41,319.3
XS Rating Curve= 0 ,0
Exp/Cntr(USF)=0,0
Exp/Cntr=0.3,0.1

Type RM Length L Ch R = 1 ,467     ,257.4,243.6,226.6
XS GIS Cut Line= 4
1669190.28350912365499.0384802711669112.35900718365654.887484151
1668808.30065647365705.3092207011668756.35098851365974.225148965
#Sta/Elev= 30
       0   928.6      24  911.47      33  907.28    41.9  901.38    55.3  895.36
    77.7   888.5    82.2  885.01   107.1  859.48     118     843   126.9  834.84
   140.3  830.32   154.8  828.77   263.7  829.49   267.7  828.92  275.47  824.05
     284  823.13   301.1  824.06   316.4  824.16   324.5  828.76   332.6   829.9
   450.2  832.15   478.5  830.72   542.8  830.91   660.9  836.84   669.1  839.71
   677.2  846.04   697.6  858.73   713.9  865.89   742.4  886.54 756.343  894.02
#Mann= 7 ,-1,0
       0      .1       0  275.47    .045       0   301.1      .1       0
  364.24     .05       0  464.24     .07       0  542.46     .06       0
  642.46      .1       0
#XS Ineff= 2 , 0
                          481.94          845.15
Permanent Ineff=
       F       F
Bank Sta=275.47,301.1
XS Rating Curve= 0 ,0
Exp/Cntr(USF)=0,0
Exp/Cntr=0.3,0.1

Type RM Length L Ch R = 1 ,223     ,36.7,36.7,37
XS GIS Cut Line= 3
1668993.18035715365433.3374296151668828.16376481365463.896057827
1668738.01581158365958.945834859
#Sta/Elev= 30
       0  911.34     9.2  904.86    25.5  897.69    41.8   895.6    48.3  894.02
      58  889.83    86.5  875.32   106.9  860.44   135.3  836.54   139.4  834.02
   151.6  832.13     201  831.15   205.1  829.67   213.1  824.91   217.3   824.3
   233.8  822.95   237.6  822.98   241.7  824.29   247.5  826.88   257.4  828.02
   264.7  831.29   271.6  832.08   465.3  832.55   554.7  834.37   577.7  836.35
   591.1  840.76   607.6  848.62   623.8  859.66   648.2  873.36 671.013  888.52
#Mann= 6 ,-1,0
       0      .1       0  167.82     .07       0   217.3    .045       0
   241.7     .07       0  477.82     .06       0  577.82      .1       0
#XS Ineff= 2 , 0
          199.67  840.22
Permanent Ineff=
       F       F
Bank Sta=217.3,241.7
XS Rating Curve= 0 ,0
Exp/Cntr(USF)=0,0
Exp/Cntr=0.3,0.1

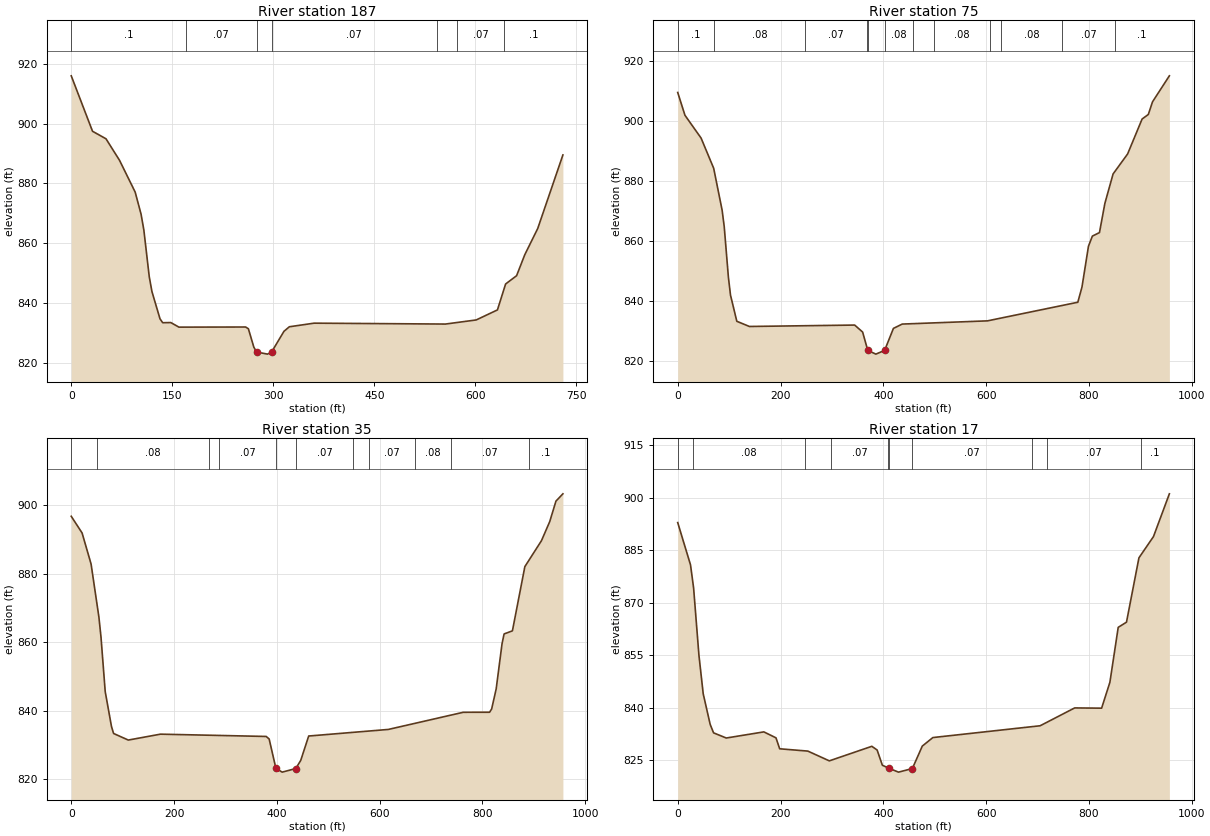
Type RM Length L Ch R = 1 ,187     ,103.7,112,119.1
XS GIS Cut Line= 3
1668991.65242574365407.362595635  1668799.133068 365419.58604692
1668704.40132055365948.250314985
#Sta/Elev= 30
       0  916.02    31.6  897.45    51.6  894.93    71.7  887.72    94.9  877.09
   103.7  869.65   107.8  864.39   115.8  848.77   119.8  843.78   131.8  834.62
   135.8  833.33   147.8  833.38   159.9  831.85   258.9  831.89     263  831.31
   271.1  825.15   275.1  823.53   291.4  822.81  297.56  823.54   315.8  830.44
   323.8  831.97   360.5  833.18   555.5  832.88   601.3  834.26   632.8  837.62
   644.9  846.29   661.2  849.07   673.4  856.11   692.6  864.88729.9918  889.52
#Mann= 7 ,-1,0
       0      .1       0     170     .07       0   275.1    .045       0
  297.56     .07       0  542.91     .06       0  572.91     .07       0
  642.91      .1       0
Bank Sta=275.1,297.56
XS Rating Curve= 0 ,0
Exp/Cntr(USF)=0,0
Exp/Cntr=0.3,0.1

Type RM Length L Ch R = 1 ,75      ,40.1,40,42.4
XS GIS Cut Line= 4
1668988.59656292365376.8039674231668794.54927377365335.549819337
 1668438.5412551365771.0102713561668464.51608908365965.057560501
#Sta/Elev= 30
       0  909.57    14.1  901.97    45.5  894.37      70  884.31    86.4  870.37
    90.5  864.88    98.6  848.07   102.7  842.08     115  833.35   139.5  831.62
   344.3  832.09   359.8  829.76   369.8  823.66   385.5  822.41   402.6  823.65
   419.7  830.98   436.8  832.42   602.7  833.49   778.5  839.69   786.6  844.76
   799.2  858.34   806.8  861.72   820.6  862.89   831.2  872.66   847.1  882.42
   875.4  889.09   903.6  900.73   915.7  902.24   923.8  906.44956.6277  915.11
#Mann= 12 ,-1,0
       0      .1       0      70     .08       0  248.38     .07       0
  368.38     .08       0   369.8    .045       0   402.6     .08       0
  458.38     .07       0  498.38     .08       0  608.38     .07       0
  628.38     .08       0  748.38     .07       0  850.85      .1       0
Bank Sta=369.8,402.6
XS Rating Curve= 0 ,0
Exp/Cntr(USF)=0,0
Exp/Cntr=0.3,0.1

Type RM Length L Ch R = 1 ,35      ,21,17.5,25.2
XS GIS Cut Line= 4
1668968.73345458 365341.661544981668774.68616543365300.407396894
1668418.67814677365735.8678489131668444.65298075365929.915138058
#Sta/Elev= 30
       0  896.71    21.1  891.84    38.6  882.79    53.8  867.33    57.9  861.45
    66.1  845.58    78.3   835.4    82.4  833.37     111  831.45   173.5  833.17
   379.4   832.5   385.1  831.75  398.22  823.19   410.4   822.1   436.8  823.14
   446.5  825.51     462  832.63     617  834.55   762.7  839.55     814  839.56
     818  840.52   826.8  846.37   838.2  859.54   842.2   862.4   858.4   863.3
   882.6  882.03   914.9  889.59     931  895.16   943.1  901.13956.6277  903.26
#Mann= 11 ,-1,0
       0      .1       0      50     .08       0  268.38      .1       0
  288.38     .07       0  398.22    .045       0   436.8     .07       0
  548.38     .08       0  578.38     .07       0  668.38     .08       0
  738.38     .07       0  890.85      .1       0
Bank Sta=398.22,436.8
XS Rating Curve= 0 ,0
Exp/Cntr(USF)=0,0
Exp/Cntr=0.3,0.1

Type RM Length L Ch R = 1 ,17      ,,,
XS GIS Cut Line= 4
 1668956.5100033365330.9660251061668762.46271415 365289.71187702
1668406.45469548365725.1723290381668432.42952946365919.219618184
#Sta/Elev= 30
       0  892.92    24.9  880.85    30.9  874.27    41.3  854.99    49.6     844
    63.1  835.28    69.8  832.82    94.5  831.35   167.6   833.1   191.2   831.4
   198.4  828.27   253.2  827.61     295  824.82   377.7  828.98     388  827.92
   398.2  823.57  411.84  822.65   429.6   821.6  456.55  822.62   475.9  829.04
   496.5  831.48   705.2  834.85   772.4  839.95   824.8  839.88   840.9  847.27
   857.1  862.98   873.2  864.46   897.4  882.84   925.7  888.92956.6277  901.14
#Mann= 10 ,-1,0
       0      .1       0      30     .08       0  248.38      .1       0
  298.38     .07       0  408.38      .1       0  411.84    .045       0
  456.55     .07       0  688.38     .08       0  718.38     .07       0
  900.85      .1       0
Bank Sta=411.84,456.55
XS Rating Curve= 0 ,0
Exp/Cntr(USF)=0,0
Exp/Cntr=0.3,0.1
LCMann Table=0

Chan Stop Cuts=-1
Use User Specified Reach Order=0
Composite Channel Slope=5