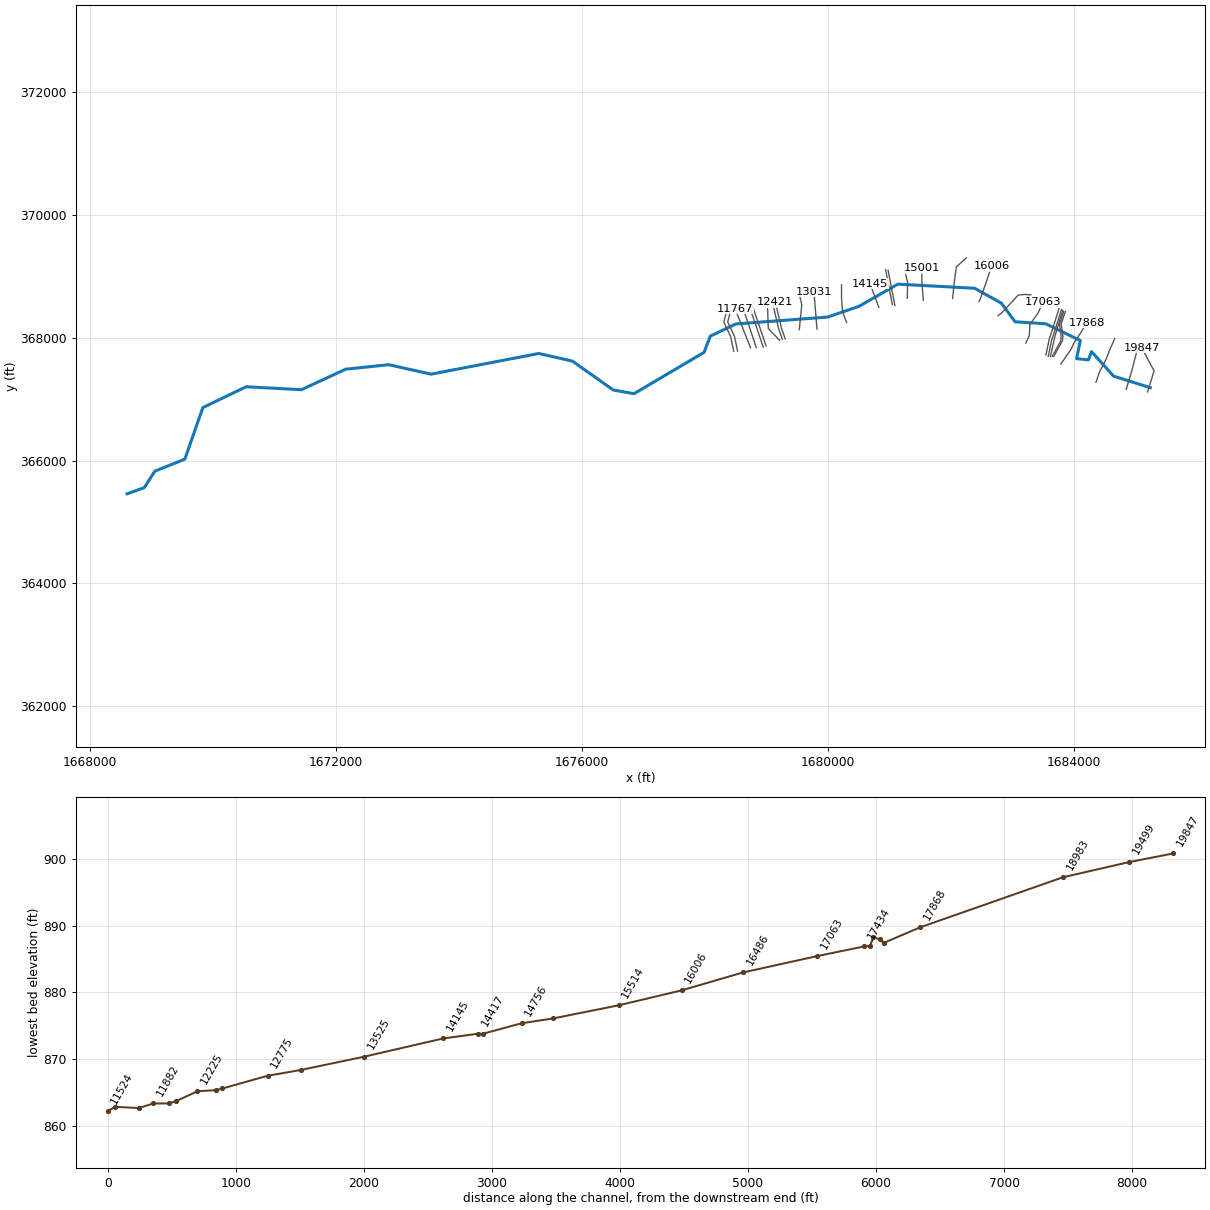
--- PRICERN.prj (project) ---

Proj Title=PRICERN
Current Plan=p01
Default Exp/Contr=0,0
English Units
Geom File=g01
Flow File=f01
Plan File=p01
BEGIN DESCRIPTION:
---------- MODELED AS PART OF WVEMD CTP PROGRAM, 2023----------
Stream Name: Price Run
Flood Zone:  AFH
Wetzel County, WV
HEC-RAS Version: RAS 6.3
Vertical Datum: NAVD88
Projection: NAD 1983 StatePlane West Virginia S FIPS 4702 (US Feet)
Terrain: 1-meter West Virginia FEMA R3 South Central (collected 2018-2020)
Land Use: 2019 NLCD
Hydrologic Method:
WV 2010 Regional Regression Equations
Additional Model Notes:
None
END DESCRIPTION:
DSS File=dss
DSS Export Rating Curves= 0
DSS Export Rating Curve Sorted= 0
DSS Export Volume Flow Curves= 0
DXF OffsetX= 0
DXF OffsetY= 0
DXF ScaleX= 0
DXF ScaleY= 0

--- PRICERN.p01 (plan) ---

Plan Title=Floodplain
Program Version=6.30
Short Identifier=Floodplain
Geom File=g01
Flow File=f01
Subcritical Flow
K Sum by GR= 0
Std Step Tol= 0.01
Critical Tol= 0.01
Num of Std Step Trials= 20
Max Error Tol= 0.3
Flow Tol Ratio= 0.001
Split Flow NTrial= 30
Split Flow Tol= 0.02
Split Flow Ratio= 0.02
Log Output Level= 0
Friction Slope Method= 1
Unsteady Friction Slope Method= 2
Unsteady Bridges Friction Slope Method= 1
Parabolic Critical Depth
Global Vel Dist= 0 , 0 , 0
Global Log Level= 0
CheckData=False
Encroach Param=-1 ,0,0, 0
Computation Interval=0.1SEC
Output Interval=1SEC
Instantaneous Interval=Max Profile
Mapping Interval=1HOUR
Computation Time Step Use Courant=        0
Computation Time Step Use Time Series=    0
Computation Time Step Count To Double=0
Computation Time Step Max Doubling=0
Computation Time Step Max Halving=0
Computation Time Step Residence Courant=0
Run HTab= 0
Run UNet= 0
Run Sediment= 0
Run PostProcess= 0
Run WQNet= 0
Run RASMapper=-1
UNET Theta= 0
UNET Theta Warmup= 0
UNET ZTol= 0
UNET ZSATol= 0
UNET MxIter= 0
UNET Max Iter WO Improvement= 0
UNET MaxInSteps= 0
UNET DtIC= 0
UNET DtMin= 0
UNET MaxCRTS= 0
UNET WFStab= 0
UNET SFStab= 0
UNET WFX= 1
UNET SFX= 1
UNET Gravity=32.17405
UNET 1D Methodology=Finite Difference
UNET DSS MLevel= 1
UNET Pardiso=0
UNET DZMax Abort= 0
UNET Use Existing IB Tables= 0
UNET Froude Reduction=False
UNET Froude Limit= 0
UNET Froude Power= 0
UNET D1 Cores= 0
UNET WindReference=Eulerian
UNET WindDragFormulation=Hsu (1988)
UNET D2 Coriolis=0
UNET D2 Cores= 0
UNET D2 Theta= 1
UNET D2 Theta Warmup= 1
UNET D2 Z Tol= 0.01
UNET D2 Volume Tol= 0.01
UNET D2 Max Iterations= 20
UNET D2 Equation= 0
UNET D2 RampUpFraction=0.1
UNET D2 TimeSlices= 1
UNET D2 Turbulence Formulation=Non-Conservative (original)
UNET D2 Eddy Viscosity=0.3
UNET D2 Transverse Eddy Viscosity=0.1
UNET D2 Smagorinsky Mixing=0
UNET D2 BCVolumeCheck=0
UNET D2 Cores=0
UNET D2 SolverType=PARDISO (Direct)
UNET D2 Minimum Iterations= 3
UNET D2 Maximum Iterations= 30
UNET D2 Restart Number= 10
UNET D2 Relaxation Coeff=1.3
UNET D2 SOR Precondition Iterations= 10
UNET D2 ILUT Maximum Fill= 8
UNET D2 ILUT Tolerance=1E-08
UNET D2 Convergence Tolerance=0.00001
UNET D1D2 MaxIter= 0
UNET D1D2 ZTol=0.01
UNET D1D2 QTol=0.1
UNET D1D2 MinQTol=1
DSS File=dss
Write IC File= 0
Write IC File at Fixed DateTime=0
Write IC File at Sim End=0
Echo Input=False
Echo Parameters=False
Echo Output=False
Write Detailed= 0
HDF Write Warmup=0
HDF Write Time Slices=0
HDF Flush=0
HDF Compression= 1
HDF Chunk Size= 1
HDF Spatial Parts= 1
HDF Use Max Rows=0
HDF Fixed Rows= 1
Calibration Method= 0
Calibration Iterations= 20
Calibration Max Change=0.05
Calibration Tolerance=0.2
Calibration Maximum=1.5
Calibration Minimum=0.5
Calibration Optimization Method= 1
WQ AD Non Conservative
WQ ULTIMATE=-1
WQ Max Comp Step=1HOUR
WQ Output Interval=15MIN
WQ Output Selected Increments= 0
WQ Output face flow=0
WQ Output face velocity=0
WQ Output face area=0
WQ Output face dispersion=0
WQ Output cell volume=0
WQ Output cell surface area=0
WQ Output cell continuity=0
WQ Output cumulative cell continuity=0
WQ Output face conc=0
WQ Output face dconc_dx=0
WQ Output face courant=0
WQ Output face peclet=0
WQ Output face adv mass=0
WQ Output face disp mass=0
WQ Output cell mass=0
WQ Output cell source sink temp=0
WQ Output nsm pathways=0
WQ Output nsm derived pathways=0
WQ Create Restart=0
WQ Fixed Restart=0
WQ System Summary=0
WQ Write To DSS=0
Sorting and Armoring Iterations= 10
XS Update Threshold= 0.02
Bed Roughness Predictor= 0
Hydraulics Update Threshold= 0.02
Energy Slope Method= 1
Volume Change Method= 1
Sediment Retention Method= 0
Sediment TS Multiplier= 1
Warm Up Method= 0
XS Weighting Method= 0
Number of US Weighted Cross Sections= 1
Number of DS Weighted Cross Sections= 1
Upstream XS Weight=0
Main XS Weight=1
Downstream XS Weight=0
Number of DS XS's Weighted with US Boundary= 1
Upstream Boundary Weight= 1
Weight of XSs Associated with US Boundary= 0
Number of US XS's Weighted with DS Boundary= 1
Downstream Boundary Weight= 0.5
Weight of XSs Associated with DS Boundary= 0.5
Percentile Method= 0
Sediment Output Level= 3
Mass or Volume Output= 0
Output Increment Type= 1
Profile and TS Output Increment= 1
Transport Output Increment 1
XS Output Flag= 0
XS Output Increment= 10
Read HDF5 Sediment Hotstart= 0
Sediment Hotstart Type= 0
Write Gradation File= 0
Read Gradation Hotstart= 0
Write HDF5 File= 1
Write Binary Output= 1
Write DSS Sediment File= 0
DSS Sediment Output Type= 1
SV Curve= 0
Specific Gage Flag= 0
Subcell Erosion Methods= 0
Subcell Deposition Methods= 0
Advection Scheme= 1
Matrix Solver= 0
Implicit Weighting Factor= 1
Maximum Outer Loop Convergence Iterations= 5
Convergence Maximum Absolute= 0.001
Convergence RMSE= 0.0001
Grain Fractions Max Abs Error= 0.001
Max Subgrid Regions= 1
Max Subgrid Length Scale= 3.402823E+38
Initial Layer Thickness= 3.402823E+38
Min Layer Thickness= 3.402823E+38
Max Layer Thickness= 3.402823E+38
Number of Layers= 5

--- PRICERN.f01 (steady flow) ---

Flow Title=Flow
Program Version=6.31
Number of Profiles= 1
Profile Names=F01pct
River Rch & RM=PRICERN,Main,19847
    2200
River Rch & RM=PRICERN,Main,14456
    2460
River Rch & RM=PRICERN,Main,12421
    2770
River Rch & RM=PRICERN,Main,7997
    3090
Boundary for River Rch & Prof#=PRICERN,Main            , 1
Up Type= 0
Dn Type= 3
Dn Slope=0.00327
DSS Import GetInterval= 0
DSS Import GetPeak= 0
DSS Import FillOption= 0

--- PRICERN.g01 (geometry) ---

Geom Title=Geometry
Program Version=6.30

River Reach=PRICERN         ,Main
Reach XY= 30
1685244.16899982367184.811000556     1684643.758      367374.434
     1684287.148      367772.605     1684237.052       367637.16
     1684044.831      367657.569     1684104.575       367952.58
     1683544.612      368224.212     1683044.393      368257.981
     1682821.744      368560.041     1682387.879      368802.451
     1681138.375       368869.71     1680505.216      368507.904
     1679996.138      368333.959     1678504.851      368222.055
     1678088.543      368023.758     1677987.075      367759.362
     1676848.316      367087.355     1676513.763      367145.917
     1675845.235      367617.887     1675300.208      367741.388
     1673548.584      367405.094     1672859.182      367558.745
     1672161.663      367486.269     1671440.372      367152.295
     1670542.632      367200.025     1669837.946      366861.598
     1669545.162      366022.581     1669056.447      365825.907
     1668885.749      365558.3571668604.61584623365458.198154496

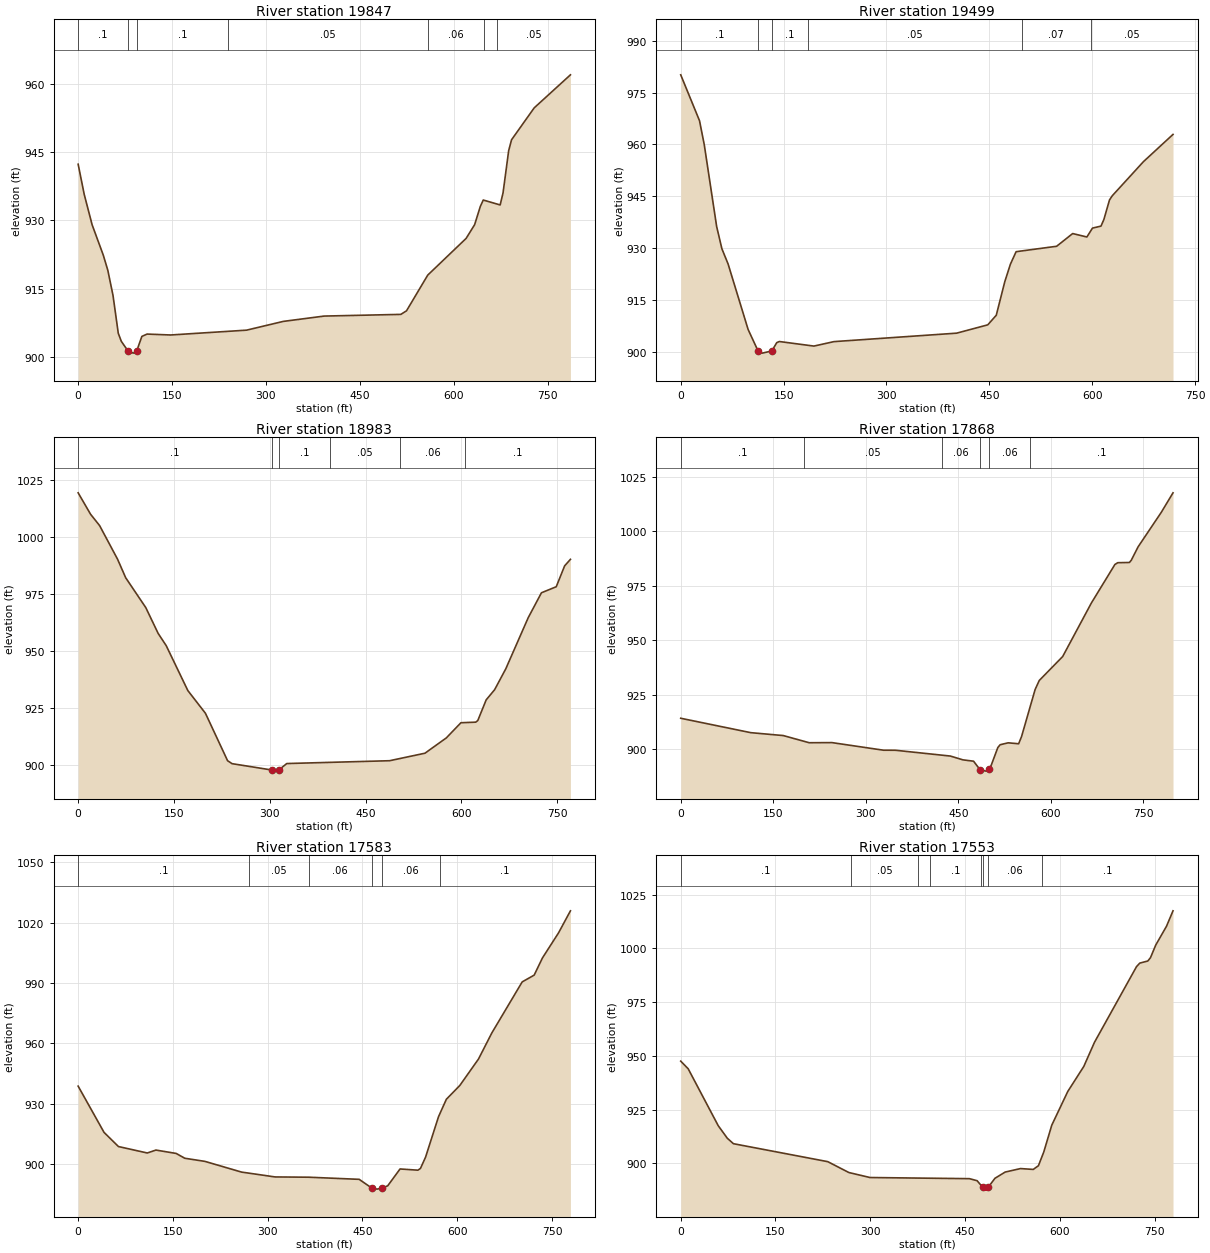
Type RM Length L Ch R = 1 ,19847   ,348.6,347.9,348.1
XS GIS Cut Line= 3
1685199.17680125367115.2633381431685304.37487887367458.085308737
1685102.64209473367835.560763725
#Sta/Elev= 30
       0  942.32     9.7  935.69    22.3  929.04    40.2  922.35    47.4  919.05
    55.7  913.53    64.1  905.23      69  903.45    80.1  901.26    88.2  900.87
    93.4  901.27   101.8  904.54   110.1  905.05   147.8  904.85   269.1  905.91
   327.7  907.83   393.1     909   515.6  909.37   524.7  910.16   558.6  917.99
   619.9  926.04   633.5  929.05   642.6  933.05   647.3  934.46   674.3  933.38
   678.9  936.03   687.9  945.29   692.5  947.68   728.7  954.68   786.6  961.93
#Mann= 7 ,-1,0
       0      .1       0    80.1    .045       0    93.4      .1       0
     240     .05       0   558.6     .06       0   648.6     .07       0
   668.6     .05       0
Bank Sta=80.1,93.4
XS Rating Curve= 0 ,0
Exp/Cntr(USF)=0,0
Exp/Cntr=0.3,0.1

Type RM Length L Ch R = 1 ,19499   ,518.8,516,513.7
XS GIS Cut Line= 6
1684851.70660792367158.3063359261684873.15768051367230.175942838
 1684901.1422046   367326.1803441684922.76781751367397.994832918
1684948.00103475367481.7745210081685042.10577723 367850.29619842
#Sta/Elev= 30
       0  980.14    27.4  966.85    34.3  959.93    52.4  936.19      60   929.8
    69.1  925.35    98.3  906.39   112.7900.2204   119.1  899.56   132.9   900.2
     140   902.6   143.8  902.92   194.2   901.6   223.4  902.89   402.3  905.34
   447.7  907.75   460.1  910.53   472.5  920.24   480.7  925.31     489  928.93
   548.1   930.5   571.5  934.18   592.2  933.19   600.4  935.76   612.8  936.34
     617  938.26   625.2  943.91   629.3  945.14   674.7     955   717.8  962.89
#Mann= 6 ,-1,0
       0      .1       0   112.7    .045       0   132.9      .1       0
     185     .05       0   497.5     .07       0   597.5     .05       0
Bank Sta=112.7,132.9
XS Rating Curve= 0 ,0
Exp/Cntr(USF)=0,0
Exp/Cntr=0.3,0.1

Type RM Length L Ch R = 1 ,18983   ,1108.8,1115.3,1108.6
XS GIS Cut Line= 6
1684359.77435063367274.2027074211684419.25637292367446.474474637
1684504.40803616367606.7720854731684537.64315214367679.482951816
1684579.92418179367794.2435194421684663.80869965367980.867297277
#Sta/Elev= 30
       0 1019.53    19.4 1010.14    33.6 1005.13    61.7  990.37    74.4  982.23
   105.9   969.1   125.2  957.79   137.9  952.37   171.7  932.67   199.3  922.67
   233.9  901.86   240.9  900.56   303.9  897.74   308.9  897.28   314.8  897.96
   326.6  900.61   487.5  901.85   542.9  905.15   576.3  911.87   599.2  918.54
   622.4  918.79   625.6  919.52   638.7  928.58   651.9  933.04   669.4  942.23
   704.5  964.67   725.2  975.62   748.4  978.28   761.5  987.45   770.6  990.32
#Mann= 6 ,-1,0
       0      .1       0   303.9    .045       0   314.8      .1       0
  393.78     .05       0  503.73     .06       0  606.03      .1       0
Bank Sta=303.9,314.8
XS Rating Curve= 0 ,0
Exp/Cntr(USF)=0,0
Exp/Cntr=0.3,0.1

Type RM Length L Ch R = 1 ,17868   ,279.8,284.9,291
XS GIS Cut Line= 6
1683789.35777926 367571.193571051683957.59191873367813.555098114
1683996.31007801367904.6699913731684085.86634033368039.074426047
1684113.53727423 368081.741337151684214.23994476368244.686521102
#Sta/Elev= 30
       0  914.08   113.6  907.45   166.2  906.12   208.3  902.82   245.1  902.88
   328.7  899.38     348  899.36   437.1  896.69   457.3  894.95   474.6  894.33
   484.9890.5025   494.7  889.76   499.6  890.51   503.4  892.57     514  900.64
   517.8  901.91   530.7  902.78   547.7  902.34   552.4  905.65   574.4   927.3
   581.1  931.45   619.1  942.49   665.5  967.06   703.7  984.81   708.4  985.64
   727.2  985.74   730.2  986.74   741.3  992.93     779 1008.86   797.9 1017.78
#Mann= 6 ,-1,0
       0      .1       0     200     .05       0  424.03     .06       0
   484.9    .045       0   499.6     .06       0  565.54      .1       0
Bank Sta=484.9,499.6
XS Rating Curve= 0 ,0
Exp/Cntr(USF)=0,0
Exp/Cntr=0.3,0.1

Type RM Length L Ch R = 1 ,17583   ,30.8,30,28.5
XS GIS Cut Line= 5
1683675.53502414367696.6155366721683814.87916013 367950.24191369
1683821.89649072368025.4275985761683793.82716836368220.910379282
1683862.99799845368426.417917972
#Sta/Elev= 30
       0  938.65      41  915.64    63.8   908.6   109.4   905.4   123.1  906.85
   155.1  905.18   168.8  902.78   200.7  901.22   258.7  895.89   311.8  893.48
   364.9  893.35   444.8  892.29   464.8  887.95   473.1  887.42   481.2  887.95
     490  889.08   509.5  897.45   537.8  896.84   541.8  897.71   549.9  903.34
   570.4  923.45   582.8  932.12   604.2  939.03   633.7  952.16   654.8  965.13
   702.8   990.5   721.8  993.89     735 1002.49   760.4 1014.92   779.2 1025.87
#Mann= 6 ,-1,0
       0      .1       0     270     .05       0   364.9     .06       0
   464.8    .045       0   481.2     .06       0  572.38      .1       0
Bank Sta=464.8,481.2
XS Rating Curve= 0 ,0
Exp/Cntr(USF)=0,0
Exp/Cntr=0.3,0.1

Type RM Length L Ch R = 1 ,17553   ,50.4,48.6,48.1
XS GIS Cut Line= 5
1683647.96693968367692.6056334781683787.31107567367946.232010496
1683794.32840626368021.417695382 1683766.2590839368216.900476088
  1683835.429914368422.408014779
#Sta/Elev= 30
       0  947.55    11.8     944    59.3  917.53    73.7  911.67    83.4  909.12
   232.7  900.76   266.1   895.7   299.6  893.37     457  892.84   469.1  891.89
     478  888.82   481.2  887.97   486.7888.8475   497.4  893.02   513.5  895.91
   537.8  897.54     558  897.14   566.2  898.88   574.7  905.32   587.3  917.74
   612.6  933.42     638  945.09   654.9  956.33   721.4  991.53   726.6  993.19
   739.3  994.17   743.5   995.7   751.9 1001.62   768.8  1010.3   779.2 1017.53
#Mann= 8 ,-1,0
       0      .1       0     270     .05       0   374.9     .06       0
   394.9      .1       0   474.9     .06       0     478    .045       0
   486.7     .06       0  572.38      .1       0
Bank Sta=478,486.7
XS Rating Curve= 0 ,0
Exp/Cntr(USF)=0,0
Exp/Cntr=0.3,0.1

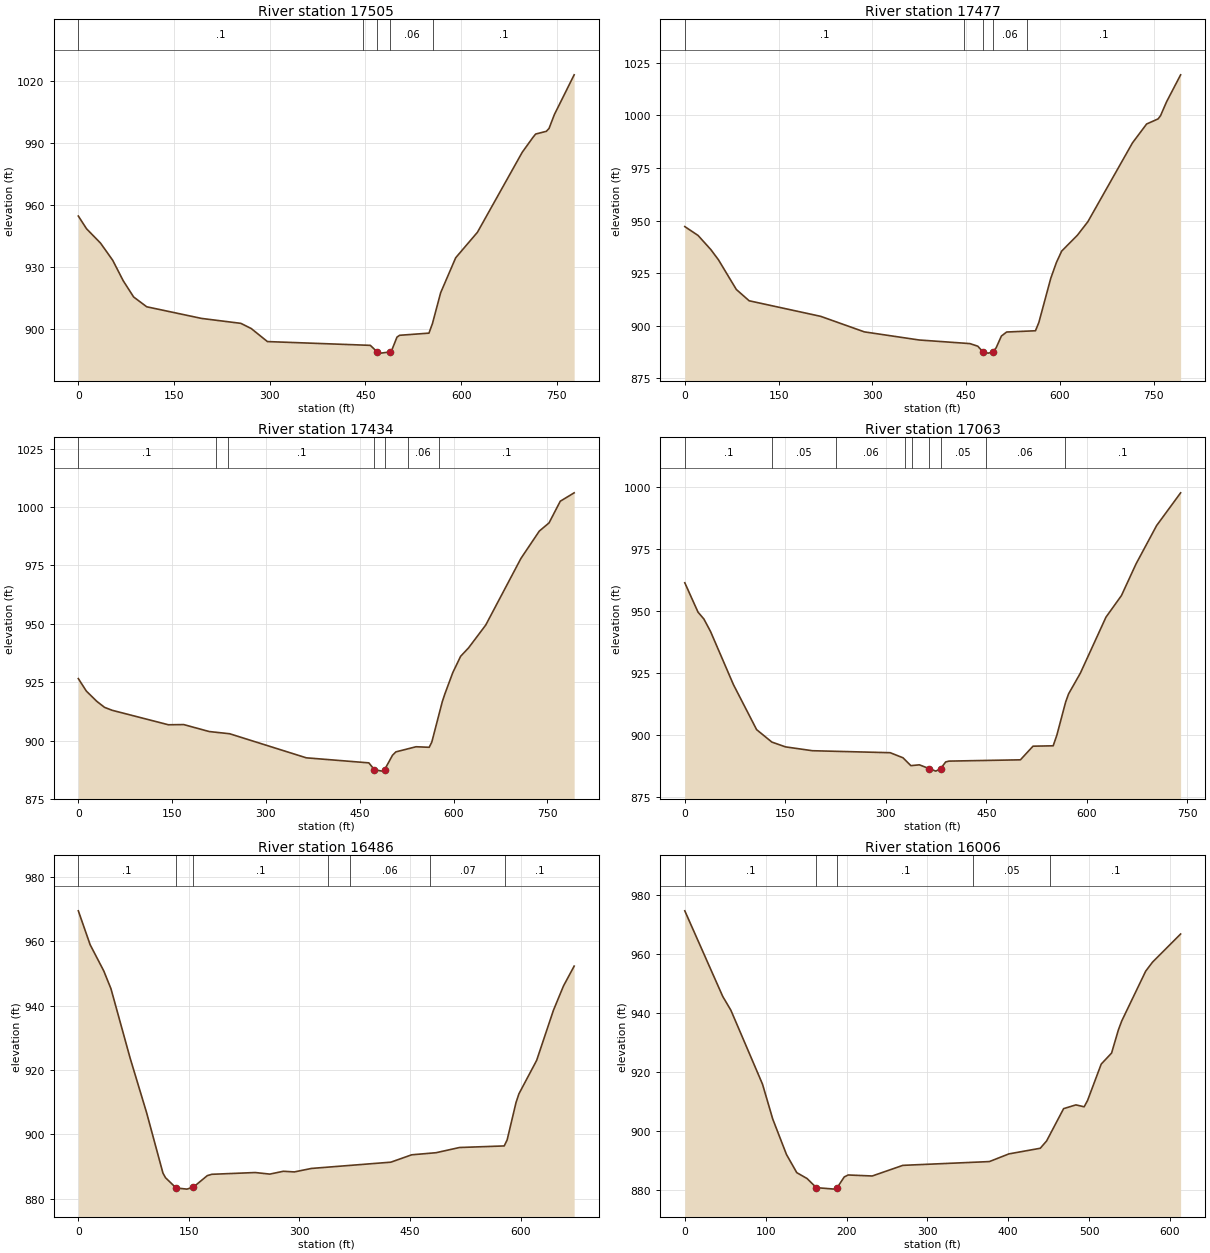
Type RM Length L Ch R = 1 ,17505   ,27.3,27.1,27.2
XS GIS Cut Line= 3
1683619.28402553367691.8974372691683693.94537529368029.301363082
1683819.61281048368442.281530027
#Sta/Elev= 30
       0  954.61    12.9  948.44    34.8  941.51    53.9   933.2    70.3  923.34
    86.7  915.44   107.2   910.7   193.2  905.07   254.7  902.69     271  900.18
   296.4  893.87   457.7  892.04   468.5  888.87   474.4  888.28   488.5888.8737
   491.1  889.51   499.5  896.04   503.6  896.91   549.6  897.95   555.1   902.6
   567.9  917.47   591.5  934.42   625.6  946.76   695.7  985.41   712.7  992.71
   716.9  994.29   733.6   995.6   737.8  996.97   746.2 1003.72   777.2 1022.93
#Mann= 5 ,-1,0
       0      .1       0  445.57     .06       0   468.5    .045       0
   488.5     .06       0  555.57      .1       0
Bank Sta=468.5,488.5
XS Rating Curve= 0 ,0
Exp/Cntr(USF)=0,0
Exp/Cntr=0.3,0.1

Type RM Length L Ch R = 1 ,17477   ,43,43.1,43.1
XS GIS Cut Line= 6
1683584.70736354367695.8000121461683640.04457696 367964.17973192
1683669.28926912368046.7094225131683692.18751728368118.129555255
1683722.14152561 368213.538157091683798.90088653368458.021263927
#Sta/Elev= 30
       0  947.13    21.2  942.93    41.6  936.21    53.8  931.36    82.4  917.24
   102.9  911.87   217.2  904.48   287.1  897.09   374.8  893.23   455.9  891.52
   468.5  890.28     477   887.5   485.2  886.99     492887.4445   497.8   889.5
   506.2   895.1   514.6  897.02   560.7  897.62   566.1  901.54   585.2  922.59
   594.2  930.08   602.6  935.48   627.8  943.04   644.5  949.46   715.8  986.92
   738.4  995.88   756.8  998.32   760.7  999.85   770.3 1006.43   792.8 1019.26
#Mann= 5 ,-1,0
       0      .1       0  446.58     .06       0     477    .045       0
     492     .06       0  546.58      .1       0
Bank Sta=477,492
XS Rating Curve= 0 ,0
Exp/Cntr(USF)=0,0
Exp/Cntr=0.3,0.1

Type RM Length L Ch R = 1 ,17434   ,373.9,371.7,368.6
XS GIS Cut Line= 6
1683545.97984396367715.5350101711683601.31705738367983.914729945
1683630.56174954368066.4444205381683653.45999771 368137.86455328
1683683.41400603368233.2731551151683760.17336696368477.756261952
#Sta/Elev= 30
       0  926.55    12.8   921.2    29.6  916.79    41.9  914.23    54.1  912.97
     144  906.77   168.5  906.85   209.3  903.87     242  902.92   364.5  892.61
   464.5  890.45   473.3  887.56   485.5  886.91   489.7  887.52   502.3  893.69
   507.8  895.16     540  897.35     561  897.12   565.2  899.36   581.9   916.6
   586.1  919.99   598.7  929.09   611.3  936.11   623.9  939.69   651.4  949.48
   707.7  978.03   737.1  989.75   752.6  993.23   770.6 1002.53   792.8 1006.13
#Mann= 7 ,-1,0
       0      .1       0     220     .06       0     240      .1       0
   473.3    .045       0   489.7      .1       0  526.58     .06       0
  576.58      .1       0
Bank Sta=473.3,489.7
XS Rating Curve= 0 ,0
Exp/Cntr(USF)=0,0
Exp/Cntr=0.3,0.1

Type RM Length L Ch R = 1 ,17063   ,573.8,577.1,570.3
XS GIS Cut Line= 6
 1683219.0119312367910.6872241451683275.05523367368031.503408417
1683281.89806776368124.3926583381683281.90266092368206.935144171
1683420.06081137368401.1230113931683498.56110696368577.213838396
#Sta/Elev= 30
       0   961.4    19.7  949.57    28.5  946.78    38.4  941.76    72.6  920.32
   107.2  902.17   129.9  897.16   150.3  895.22   190.4  893.67   306.5  892.87
   325.6  890.83   337.4  887.65   350.1  887.98     365886.4254   374.6  885.44
   381.7  886.41   389.4  889.15   394.3  889.48   500.9     890   519.7   895.5
   549.8  895.65   555.3  899.97   568.4  913.31   572.8   916.6   590.3  924.92
   628.6  947.54   651.7  956.25   673.5  969.03   704.2  984.48     740  997.67
#Mann= 9 ,-1,0
       0      .1       0     130     .05       0  226.32     .06       0
  328.87      .1       0  338.87     .05       0     365    .045       0
   381.7     .05       0  448.87     .06       0  567.19      .1       0
Bank Sta=365,381.7
XS Rating Curve= 0 ,0
Exp/Cntr(USF)=0,0
Exp/Cntr=0.3,0.1

Type RM Length L Ch R = 1 ,16486   ,474.2,479.5,483.6
XS GIS Cut Line= 5
 1682769.1792745368356.9227275481682830.54683443 368405.91213087
1683094.50624516368691.7349369061683194.69480904368702.210708555
1683298.88536506368696.152212743
#Sta/Elev= 30
       0  969.52      16     959    34.5  950.84    44.3  945.28    70.3  923.71
    92.6  906.78   114.8  887.98   118.3  886.53   132.7 883.348   147.4  882.99
   156.1883.6116   174.9  887.18   181.1   887.6     240  888.15   259.8  887.66
   278.1  888.54   293.1  888.34   316.2  889.42     424  891.37   452.3  893.66
   485.3  894.31   517.1  895.93   577.8  896.42   581.8  898.31   593.8  909.89
   597.8  912.64   621.8  923.01   644.6  938.61   658.3   946.2   672.7  952.33
#Mann= 7 ,-1,0
       0      .1       0   132.7    .045       0   156.1      .1       0
  338.52     .05       0  368.52     .06       0  477.59     .07       0
  578.32      .1       0
Bank Sta=132.7,156.1
XS Rating Curve= 0 ,0
Exp/Cntr(USF)=0,0
Exp/Cntr=0.3,0.1

Type RM Length L Ch R = 1 ,16006   ,489.8,492.4,495.5
XS GIS Cut Line= 6
1682457.81363375368584.0164286531682494.64984617368670.969666827
1682523.75838376368753.4891868271682548.11004109368824.425724748
1682633.34051367 369072.703771491682663.78008533369161.374525908
#Sta/Elev= 30
       0  974.55    46.9  945.57      57  940.88    96.1  915.85   108.8  904.01
   125.8     892   138.5  885.88   151.2  883.89   162.7   880.8   185.2   880.3
   188.5880.8187   197.2  884.43   202.1  885.09   231.8  884.75   269.7  888.35
   376.7  889.63   400.8  892.23   439.6  894.14   447.4  896.59   468.5  907.56
   483.7  908.83   493.9  908.18   498.1  910.32     515  922.65   527.8  926.37
   536.2   934.2   540.4  937.27     570  954.12   578.5  957.19   613.2   966.7
#Mann= 5 ,-1,0
       0      .1       0   162.7    .045       0   188.5      .1       0
  356.94     .05       0  451.94      .1       0
Bank Sta=162.7,188.5
XS Rating Curve= 0 ,0
Exp/Cntr(USF)=0,0
Exp/Cntr=0.3,0.1

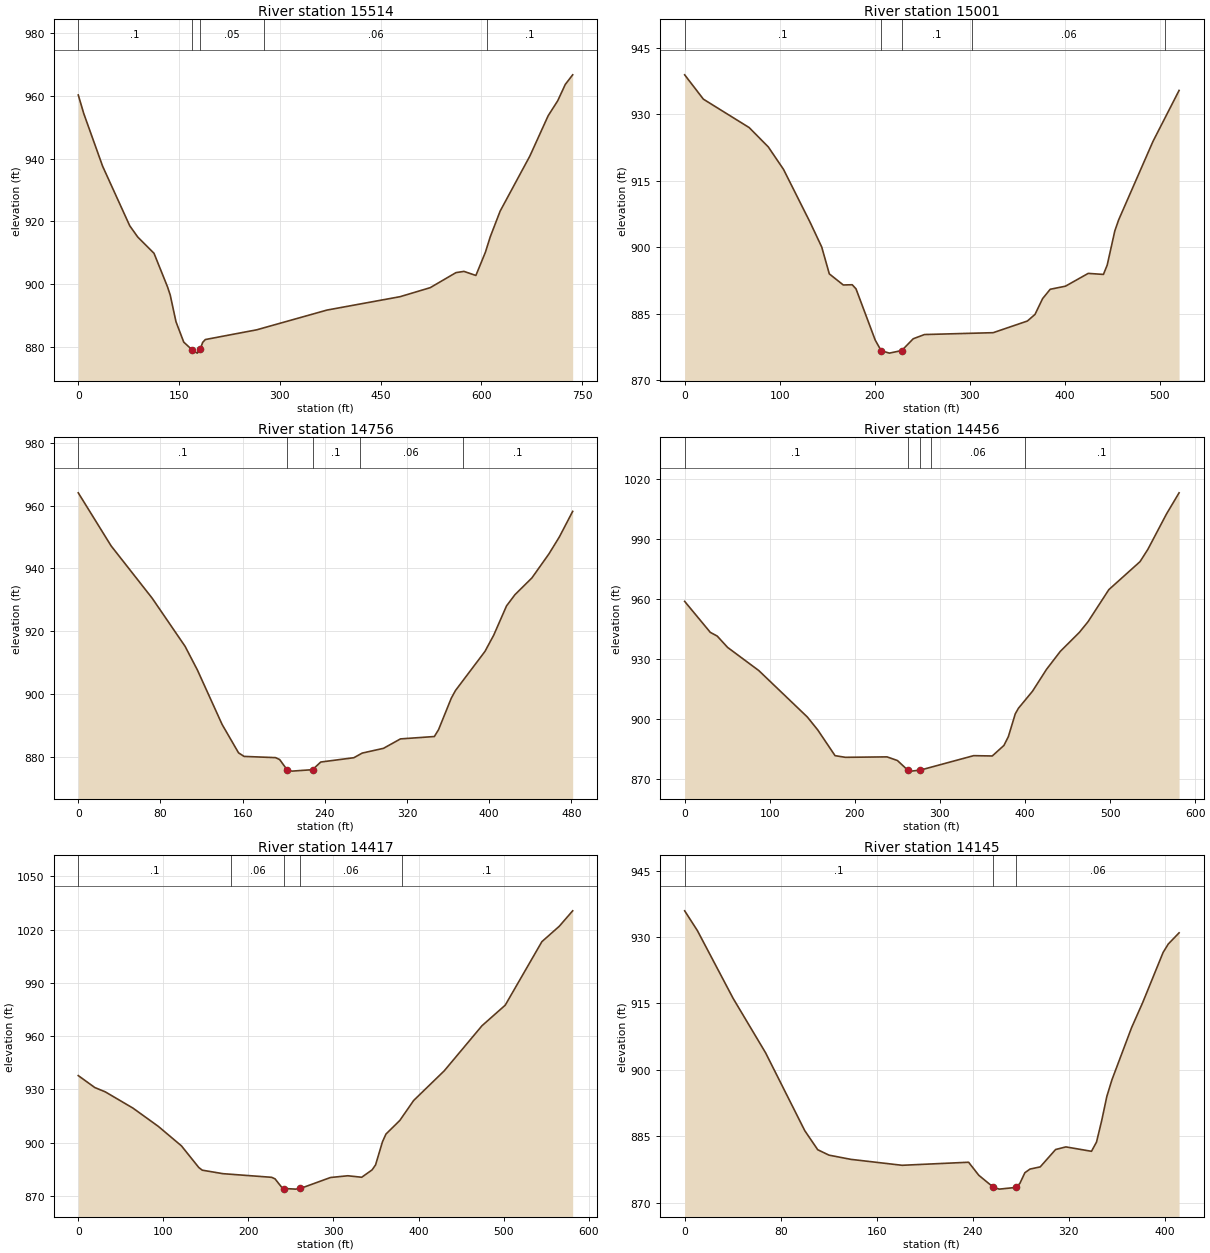
Type RM Length L Ch R = 1 ,15514   ,512.2,513.1,515.4
XS GIS Cut Line= 6
1682027.90803664368636.406064378 1682055.4499763368891.171630966
1682067.19240688368990.4850806311682077.86495773369064.768068539
1682089.90069481369151.545454042 1682251.3692488369296.741654666
#Sta/Elev= 30
       0  960.32     8.2  954.39    36.3   937.6    76.6  918.65    88.6  915.04
   112.8  909.86   132.9  899.16   136.9  896.58   145.5  888.06     157  881.58
   169.1  879.17   177.2  878.05   181.5879.2307   185.2  881.46   189.2  882.38
   265.7  885.48   370.5  891.78   479.2  896.04     524  898.91   562.3   903.7
   574.2   904.1     592   902.8   606.2  910.22   613.3  915.06   628.1   923.3
   672.5  940.92   699.6   953.7   713.8  958.46   725.1  963.68   736.1  966.74
#Mann= 5 ,-1,0
       0      .1       0   169.1    .045       0   181.5     .05       0
  276.25     .06       0  608.91      .1       0
Bank Sta=169.1,181.5
XS Rating Curve= 0 ,0
Exp/Cntr(USF)=0,0
Exp/Cntr=0.3,0.1

Type RM Length L Ch R = 1 ,15001   ,242.7,244.3,241.2
XS GIS Cut Line= 6
1681553.16235201368608.9071092611681539.08528042368770.796221167
1681531.53247401368870.5171503421681528.35170609 368945.52323392
1681529.24835785369033.4315226671681533.60464834369127.999903083
#Sta/Elev= 30
       0  938.84    19.7  933.35    67.9  926.94      88  922.58     104  917.52
   132.1  905.53   144.2  900.01   152.2  893.95   166.9  891.45   176.3   891.5
   180.3  890.57   200.5  879.02   206.7876.6431   215.4  876.08   228.4  876.67
   240.5  879.32   252.3  880.27   324.6  880.69   360.6  883.32   368.6  884.81
   376.6  888.37   384.6  890.48   400.6  891.17   424.6  894.06   440.6  893.83
   444.6  895.95   452.6  903.65   456.6  906.12   492.7  923.81   520.2  935.32
#Mann= 5 ,-1,0
       0      .1       0   206.7    .045       0   228.4      .1       0
  302.51     .06       0  505.49      .1       0
Bank Sta=206.7,228.4
XS Rating Curve= 0 ,0
Exp/Cntr(USF)=0,0
Exp/Cntr=0.3,0.1

Type RM Length L Ch R = 1 ,14756   ,292.6,300.4,299.8
XS GIS Cut Line= 3
1681292.19055832368640.5230955891681296.31597313 368904.54964334
1681242.68558061369114.945798579
#Sta/Elev= 30
       0  964.06      32  947.14      72  930.45     104  915.12     116  907.56
     140  890.24     156  881.19   161.4  880.05     192  879.66     196  879.05
   203.2 875.818     208  875.36     228  875.82     236  878.26   268.2  879.63
   276.4  881.11   297.1  882.63   313.6  885.63   346.6  886.39   350.7   888.6
   363.1  898.64   367.2  901.08   395.8   913.5   404.4  918.73   416.8  928.01
     425  931.59   441.5  936.93   458.1   944.6   468.2  949.98   481.2  958.15
#Mann= 5 ,-1,0
       0      .1       0   203.2    .045       0     228      .1       0
  274.06     .06       0  374.06      .1       0
Bank Sta=203.2,228
XS Rating Curve= 0 ,0
Exp/Cntr(USF)=0,0
Exp/Cntr=0.3,0.1

Type RM Length L Ch R = 1 ,14456   ,37.9,38.7,38.3
XS GIS Cut Line= 2
 1681090.0452327368522.9487735441680980.03417113369093.631155401
#Sta/Elev= 30
       0  958.62    30.1  943.16    38.3  941.27    50.5  935.61    87.2  924.03
   144.2  900.84   156.4   894.4   176.8  881.52     189  880.69   237.9  880.91
   250.1  879.09   262.3  874.28   266.4  873.79   277.1  874.31   339.7  881.52
   361.6  881.36   375.3  886.63   380.5     891   388.6  902.37   392.3  905.17
     409  913.78   425.3  924.61   441.6  933.64   464.1  943.18   474.2  948.48
   498.6  964.47   535.3  978.48   544.6  984.69   566.5 1002.38   581.2 1012.87
#Mann= 5 ,-1,0
       0      .1       0   262.3    .045       0   277.1      .1       0
     290     .06       0     400      .1       0
Bank Sta=262.3,277.1
XS Rating Curve= 0 ,0
Exp/Cntr(USF)=0,0
Exp/Cntr=0.3,0.1

Type RM Length L Ch R = 1 ,14417   ,270.5,272,273.5
XS GIS Cut Line= 2
1681048.79108461368537.3877253741680938.78002305369108.070107231
#Sta/Elev= 30
       0  937.76    19.5  931.02    31.7  928.62    64.3  919.44      94  909.19
   121.3  898.17   141.7  885.96   145.8  884.46   170.2  882.49   227.3  880.45
   231.3  879.58   239.5  874.61   242.3  874.14   255.8  873.79     261874.1464
   296.5  880.34   316.9  881.32   333.2  880.48   345.4  884.63   349.5  887.46
   357.6  900.46   361.7  904.81     378  912.49   394.3  923.76   430.2  940.44
   474.6  965.86   501.9  977.44     545 1013.23   565.4 1021.89   581.2 1030.61
#Mann= 5 ,-1,0
       0      .1       0     180     .06       0   242.3    .045       0
     261     .06       0     380      .1       0
Bank Sta=242.3,261
XS Rating Curve= 0 ,0
Exp/Cntr(USF)=0,0
Exp/Cntr=0.3,0.1

Type RM Length L Ch R = 1 ,14145   ,618.4,620.4,612.3
XS GIS Cut Line= 2
1680828.76896148 368490.633024211680685.75458145368877.046877949
#Sta/Elev= 30
       0   935.9    10.6  931.44    40.4  916.13    67.4  903.87   100.1  886.27
   110.9  881.97   120.3  880.75   138.5   879.8   181.2  878.46   236.6  879.15
   245.1  876.21   257.3  873.49   262.2  873.08   275.9  873.46   279.3  874.36
   283.5  876.78   287.8  877.61   296.3   878.1   309.1  882.02   317.7  882.61
     339  881.62   343.2   883.7   347.5  888.53   351.8  894.01     356  897.72
   372.4  909.52   381.8  915.27   398.7  926.51     403  928.41     412  930.93
#Mann= 3 ,-1,0
       0      .1       0   257.3    .045       0   275.9     .06       0
Bank Sta=257.3,275.9
XS Rating Curve= 0 ,0
Exp/Cntr(USF)=0,0
Exp/Cntr=0.3,0.1

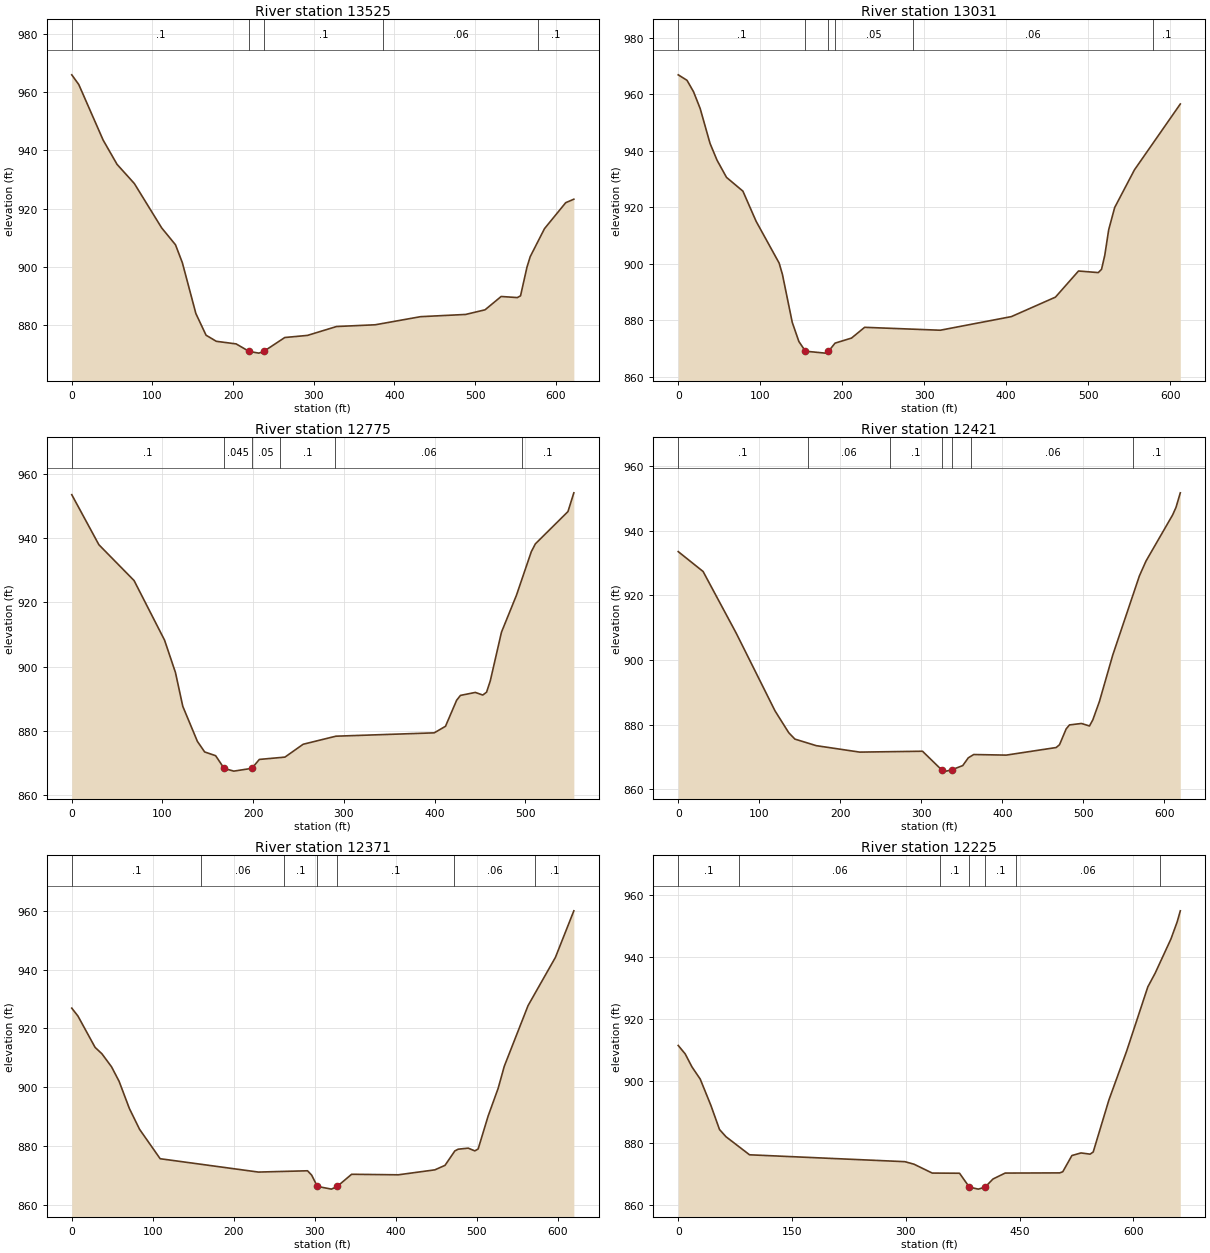
Type RM Length L Ch R = 1 ,13525   ,497.4,493.5,490.6
XS GIS Cut Line= 6
1680304.48328335368248.4301687891680267.78585019368340.437858787
1680239.14942452368427.5285638691680224.92340311368601.963254374
1680222.51067827368676.9749153671680222.66356511368858.633672786
#Sta/Elev= 30
       0  965.94     8.7   962.6    38.9  943.52    56.1   935.2    77.6  928.59
   111.5  913.34   128.6  907.56   137.1  901.41   153.9  883.91   166.5  876.49
   179.2  874.39   203.8   873.5   219.9  870.91   231.9  870.33   237.9   870.9
   264.1  875.69   292.2  876.42   328.3  879.47   376.3  880.07   432.4  882.85
   488.4  883.62   512.4  885.21   532.4  889.79   552.4  889.41   556.4  890.01
   564.4  899.88   568.4  903.47   586.1  913.09   612.4  922.01   622.5  923.21
#Mann= 5 ,-1,0
       0      .1       0   219.9    .045       0   237.9      .1       0
  385.77     .06       0  578.48      .1       0
Bank Sta=219.9,237.9
XS Rating Curve= 0 ,0
Exp/Cntr(USF)=0,0
Exp/Cntr=0.3,0.1

Type RM Length L Ch R = 1 ,13031   ,258.8,256.4,253.5
XS GIS Cut Line= 6
1679823.44529809368137.8664736991679808.74093118 368318.51932762
1679794.54410918368492.9425352011679788.45947568368567.695338452
1679781.36172085368654.9067781951679773.75510876  368748.3475362
#Sta/Elev= 30
       0  966.89    10.7  964.95    18.7  960.88    26.8  954.92    38.8   942.6
    47.3  936.68    58.9  930.57    78.9   925.7      95  915.03   123.1  900.23
   127.1  896.23   139.1  879.23   147.2  872.44   155.2  869.02   179.3  868.34
   183.3  868.98   191.3  871.88   211.4  873.67   227.4  877.48   319.7  876.45
   406.4  881.27   460.2  888.17   488.3  897.42   512.4  896.86   516.4  898.01
   520.4  903.06   525.1  911.98   532.4  919.88   556.5  933.22   612.5  956.56
#Mann= 6 ,-1,0
       0      .1       0   155.2    .045       0   183.3      .1       0
  191.25     .05       0  286.25     .06       0  578.75      .1       0
Bank Sta=155.2,183.3
XS Rating Curve= 0 ,0
Exp/Cntr(USF)=0,0
Exp/Cntr=0.3,0.1

Type RM Length L Ch R = 1 ,12775   ,350.6,353.7,355.7
XS GIS Cut Line= 3
1679535.72043133368130.7917630771679576.97457942 368535.08241432
1679542.59612268368678.096794352
#Sta/Elev= 30
       0  953.49    29.9  937.92    68.7  926.77   102.3  908.23   114.3  898.18
   122.4  887.63   138.5  876.73   146.5  873.45   158.6  872.28     168  868.32
   178.7  867.48   198.5  868.35   206.8  871.12     235  871.84   255.1  875.84
   291.2  878.35   399.6  879.39     412  881.43   424.3  889.54   428.5  891.04
   444.9  891.97   453.1  891.15   457.3  892.05   461.4  895.59   473.7   910.7
   490.2  922.18   506.6  935.76   511.1   938.2     547  948.23   553.5  954.07
#Mann= 6 ,-1,0
       0      .1       0     168    .045       0   198.5     .05       0
     230      .1       0     290     .06       0  496.39      .1       0
Bank Sta=168,198.5
XS Rating Curve= 0 ,0
Exp/Cntr(USF)=0,0
Exp/Cntr=0.3,0.1

Type RM Length L Ch R = 1 ,12421   ,50.2,49.9,47.9
XS GIS Cut Line= 3
1679306.07234032367979.5265534291679246.94139473 368151.41883712
1679146.55630105368577.711700676
#Sta/Elev= 30
       0  933.56    30.7   927.4    71.6  908.28   119.5  884.22   136.4  877.47
     144  875.49   170.3  873.46     224  871.46   301.5  871.73     325 865.994
   330.9  865.57   337.6865.9837   351.2  867.29     358  869.69   364.7  870.71
   404.8  870.53   466.5  872.88   470.6  873.75   478.8  878.64   482.9  879.88
   497.7  880.33   507.6  879.56   511.7  881.44   519.9  887.17   536.3  901.51
   569.2  926.04   577.4  930.66   610.3  944.96   614.4  947.28   619.7  951.77
#Mann= 7 ,-1,0
       0      .1       0     160     .06       0  261.78      .1       0
     325    .045       0   337.6      .1       0  361.78     .06       0
  561.78      .1       0
Bank Sta=325,337.6
XS Rating Curve= 0 ,0
Exp/Cntr(USF)=0,0
Exp/Cntr=0.3,0.1

Type RM Length L Ch R = 1 ,12371   ,147.8,145.7,142.8
XS GIS Cut Line= 3
1679259.31763915367973.3384312161679200.18669356368145.230714908
1679099.80159989368571.523578463
#Sta/Elev= 30
       0  926.88     7.6   924.2    28.8  913.53    37.2  911.36    49.1  906.92
    58.4  902.01    71.1  892.75    83.7  885.66   109.1  875.66   230.4  871.12
     291  871.56   296.1  870.08   303.1866.2491   320.5  865.32   327.6  866.23
   345.4  870.37     403  870.19   448.2  871.88   460.7  873.41   472.8  878.31
   476.9   878.9   489.3  879.26   497.5  878.33   501.6  878.99   513.9  890.17
   526.3  899.63   533.8  907.08   563.2  927.75     597  944.17   619.7  959.98
#Mann= 7 ,-1,0
       0      .1       0     160     .06       0  261.78      .1       0
   303.1    .045       0   327.6      .1       0  471.78     .06       0
  571.78      .1       0
Bank Sta=303.1,327.6
XS Rating Curve= 0 ,0
Exp/Cntr(USF)=0,0
Exp/Cntr=0.3,0.1

Type RM Length L Ch R = 1 ,12225   ,165.3,167.9,170.6
XS GIS Cut Line= 3
 1679216.6883528367956.1492028471679032.41982468368147.293422312
1679017.29330372368543.333243938
#Sta/Elev= 30
       0  911.51     9.2  908.79    18.1   904.6      29  900.66    43.1  892.14
    54.4   884.4    62.9  882.07      94  876.23   298.8  874.01   310.8  873.19
   334.8  870.33   370.8  870.28   383.7865.8005   395.5  865.15   404.4 865.775
   414.9  868.42   430.9  870.33   502.9  870.39   506.9  870.77   518.9  875.99
   530.9  876.83   542.9  876.44     547  877.14   567.7  893.94     591  909.66
     619  930.44   628.6  934.83   649.4  945.86   657.7  951.43   661.8  954.97
#Mann= 7 ,-1,0
       0      .1       0      80     .06       0   345.5      .1       0
   383.7    .045       0   404.4      .1       0   445.5     .06       0
   635.5      .1       0
Bank Sta=383.7,404.4
XS Rating Curve= 0 ,0
Exp/Cntr(USF)=0,0
Exp/Cntr=0.3,0.1

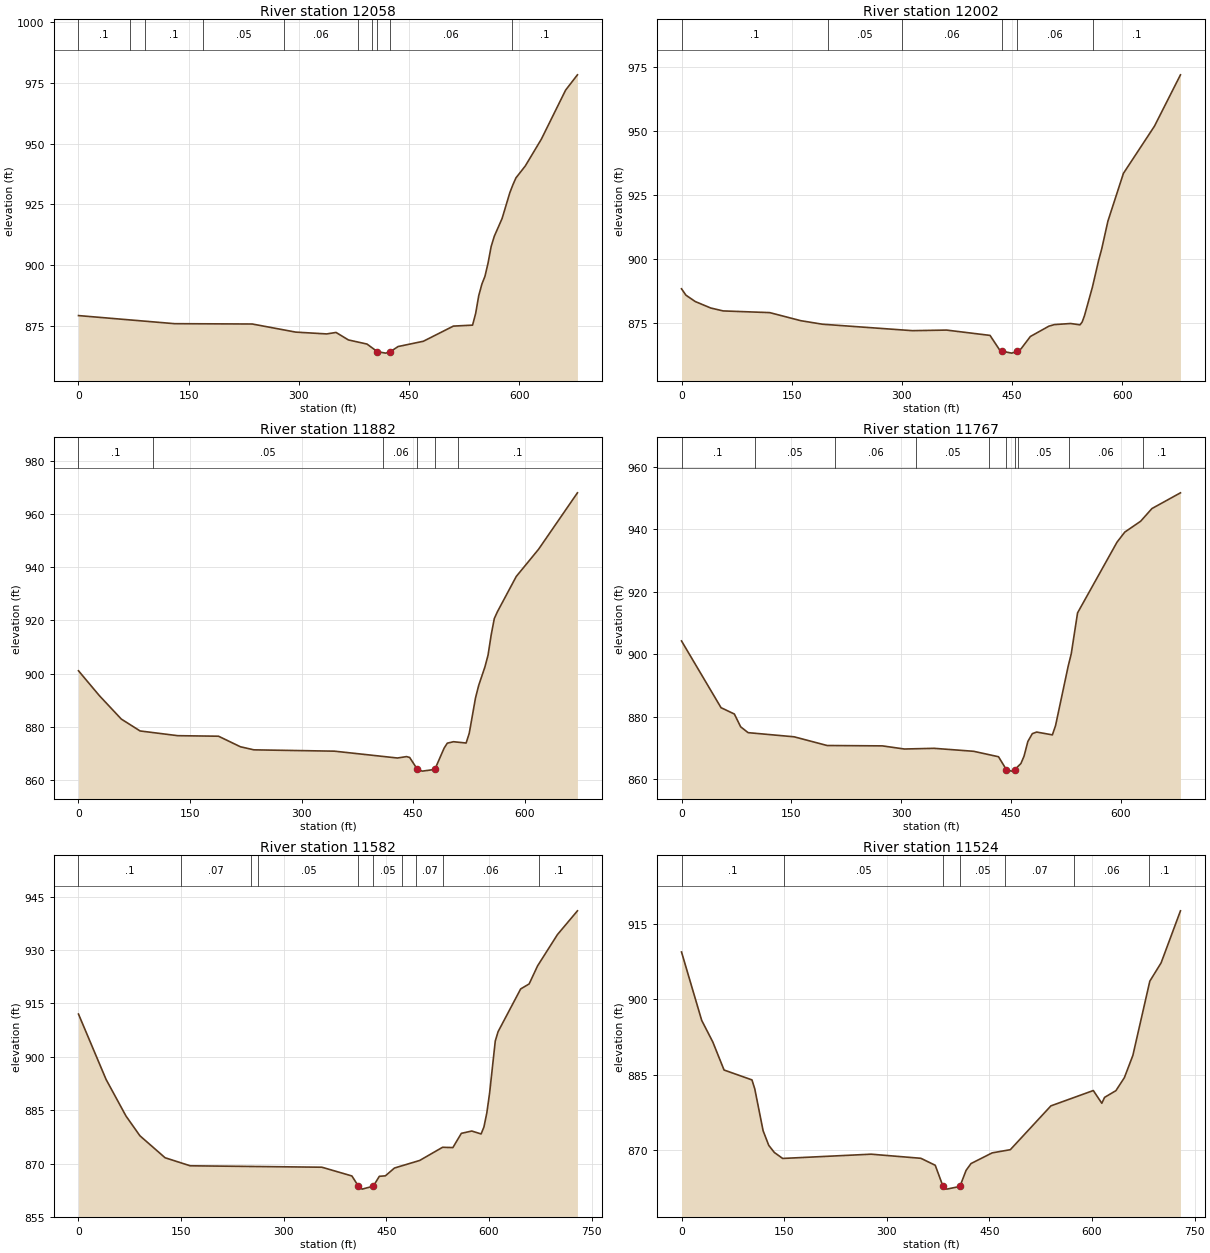
Type RM Length L Ch R = 1 ,12058   ,55.2,55.3,56.7
XS GIS Cut Line= 2
1678995.88549654 367864.540178311678777.07062787368507.780438819
#Sta/Elev= 30
       0  879.13     131  875.79   236.6  875.66   295.8  872.32     338  871.57
   350.7  872.18   367.6  869.09   392.9  867.39     407864.2607   418.3  863.66
   424.4864.2067   435.2  866.37   469.6  868.55   510.5   874.8   536.6  875.19
   540.8     880     545  887.34   549.3   892.1   553.5  895.33   557.7  900.78
   561.9  907.56   566.2  911.83   576.8  919.13   587.3  929.72   591.5  933.02
   595.7  935.88   608.3  940.74   630.3  951.84   663.3  972.03   679.4  978.33
#Mann= 10 ,-1,0
       0      .1       0      70     .05       0      90      .1       0
     170     .05       0     280     .06       0     380      .1       0
     400     .06       0     407    .045       0   424.4     .06       0
     590      .1       0
Bank Sta=407,424.4
XS Rating Curve= 0 ,0
Exp/Cntr(USF)=0,0
Exp/Cntr=0.3,0.1

Type RM Length L Ch R = 1 ,12002   ,119.8,120.4,121
XS GIS Cut Line= 2
1678950.61345475 367842.847324951678731.79858607368486.087585458
#Sta/Elev= 30
       0  888.47       6  885.98    18.7  883.49    39.8  880.96    56.7  879.82
   120.1  879.16   162.3  876.01   191.9  874.62   314.4   872.1   360.9  872.33
   420.1  870.25   432.7  864.77   436.5 864.055   449.6  863.32   457.3     864
   462.3     865     475  869.82   500.3  873.87   507.7  874.47   529.9   874.9
   542.6  874.38   545.6  875.51   548.7  877.96   559.5  889.12   567.9  899.51
   572.2  904.11   580.6  914.92   601.7  933.59     644  952.06   679.4  972.13
#Mann= 6 ,-1,0
       0      .1       0     200     .05       0     300     .06       0
   436.5    .045       0   457.3     .06       0     560      .1       0
Bank Sta=436.5,457.3
XS Rating Curve= 0 ,0
Exp/Cntr(USF)=0,0
Exp/Cntr=0.3,0.1

Type RM Length L Ch R = 1 ,11882   ,114.9,114.6,114.9
XS GIS Cut Line= 2
1678835.77505214367837.8873116671678624.00375863368474.576330461
#Sta/Elev= 30
       0  901.03    28.1  891.68    57.6  882.88    82.9  878.41   133.5  876.64
   188.3  876.44   217.8  872.47   235.9  871.32   344.2  870.82   428.9  868.25
   441.2  868.78   445.4  868.45   455.6864.0455   462.3  863.32   479.2863.9525
   491.8  872.01     496  873.83   504.4  874.37   521.3  873.88   525.5  877.54
   533.9  890.81   538.2  895.53   546.6  902.49   550.8  906.93     555   914.5
   559.2  920.65   563.4  923.23   588.7  936.46   618.7  946.68     671   967.9
#Mann= 6 ,-1,0
       0      .1       0     100     .05       0     410     .06       0
   455.6    .045       0   479.2     .06       0     510      .1       0
Bank Sta=455.6,479.2
XS Rating Curve= 0 ,0
Exp/Cntr(USF)=0,0
Exp/Cntr=0.3,0.1

Type RM Length L Ch R = 1 ,11767   ,185.1,185.5,186.1
XS GIS Cut Line= 2
1678743.11659652367833.4156495761678492.23403157 368467.22423471
#Sta/Elev= 30
       0  904.25      54  882.91    72.2  880.89    80.8   876.8      91  874.93
   153.9   873.6   198.9  870.82   274.4   870.7   304.5   869.7   345.1  869.92
   399.1  868.97   433.1  867.23     444863.0525   450.8  862.63   455.1  863.07
   463.7  865.06     468  867.42   473.2  872.11   479.3  874.61   485.2  875.12
   506.7  874.22     511  877.15   528.2  896.08   532.5  900.16   541.1  913.22
     595  935.82   605.6  939.04   627.3  942.52   642.7  946.57   681.7   951.6
#Mann= 10 ,-1,0
       0      .1       0     100     .05       0     210     .06       0
     320     .05       0     420     .06       0     444    .045       0
   455.1     .06       0     460     .05       0     530     .06       0
     630      .1       0
Bank Sta=444,455.1
XS Rating Curve= 0 ,0
Exp/Cntr(USF)=0,0
Exp/Cntr=0.3,0.1

Type RM Length L Ch R = 1 ,11582   ,57.6,57.6,57.6
XS GIS Cut Line= 4
1678531.84706814367780.598267481 1678482.8023562368018.276486907
1678371.50858678368254.0683712571678428.09863903368472.883239935
#Sta/Elev= 30
       0  912.02    40.3  893.66    69.4  883.37    89.8  877.81   126.6  871.63
   163.3  869.37   355.8  868.97   399.7  866.51   409.3  863.62   414.7  862.81
     431  863.65   439.8  866.41   448.7  866.55   461.9  868.74   498.8  870.87
   532.2  874.57   547.3  874.49   559.7  878.49   574.9  879.14   588.6  878.32
   592.7  880.27   596.9   884.2     601   889.8   609.3  904.46   613.4  907.07
   646.4  919.08   658.8  920.49   671.2  925.59   700.2  934.37   729.4  941.04
#Mann= 10 ,-1,0
       0      .1       0     150     .07       0  252.69     .06       0
  262.69     .05       0   409.3    .045       0     431     .05       0
  472.69     .06       0  492.69     .07       0  533.42     .06       0
  673.42      .1       0
Bank Sta=409.3,431
XS Rating Curve= 0 ,0
Exp/Cntr(USF)=0,0
Exp/Cntr=0.3,0.1

Type RM Length L Ch R = 1 ,11524   ,198.6,198.2,197.8
XS GIS Cut Line= 4
1678468.65484314367779.6550999441678419.61013119368017.333319369
1678308.31636178 368253.125203721678364.90641402368471.940072397
#Sta/Elev= 30
       0  909.46    29.5  895.82    45.8  891.49    62.2  885.91     103  883.94
   107.1  882.14   119.3  873.79   127.5  870.89   135.7  869.46   147.9  868.27
   277.2  869.12   349.9   868.3   370.9  866.91   382.3862.6934   387.8  862.15
     407  862.69     416  865.89   423.2  867.25   454.1  869.38   480.7  870.02
     540  878.76     602  881.82   614.4  879.28   618.5  880.46     635  881.79
   647.4  884.39   659.8  888.82   684.6  903.64   701.1  907.29   729.4  917.67
#Mann= 7 ,-1,0
       0      .1       0     150     .05       0   382.3    .045       0
     407     .05       0  472.69     .07       0  573.42     .06       0
  683.42      .1       0
Bank Sta=382.3,407
XS Rating Curve= 0 ,0
Exp/Cntr(USF)=0,0
Exp/Cntr=0.3,0.1