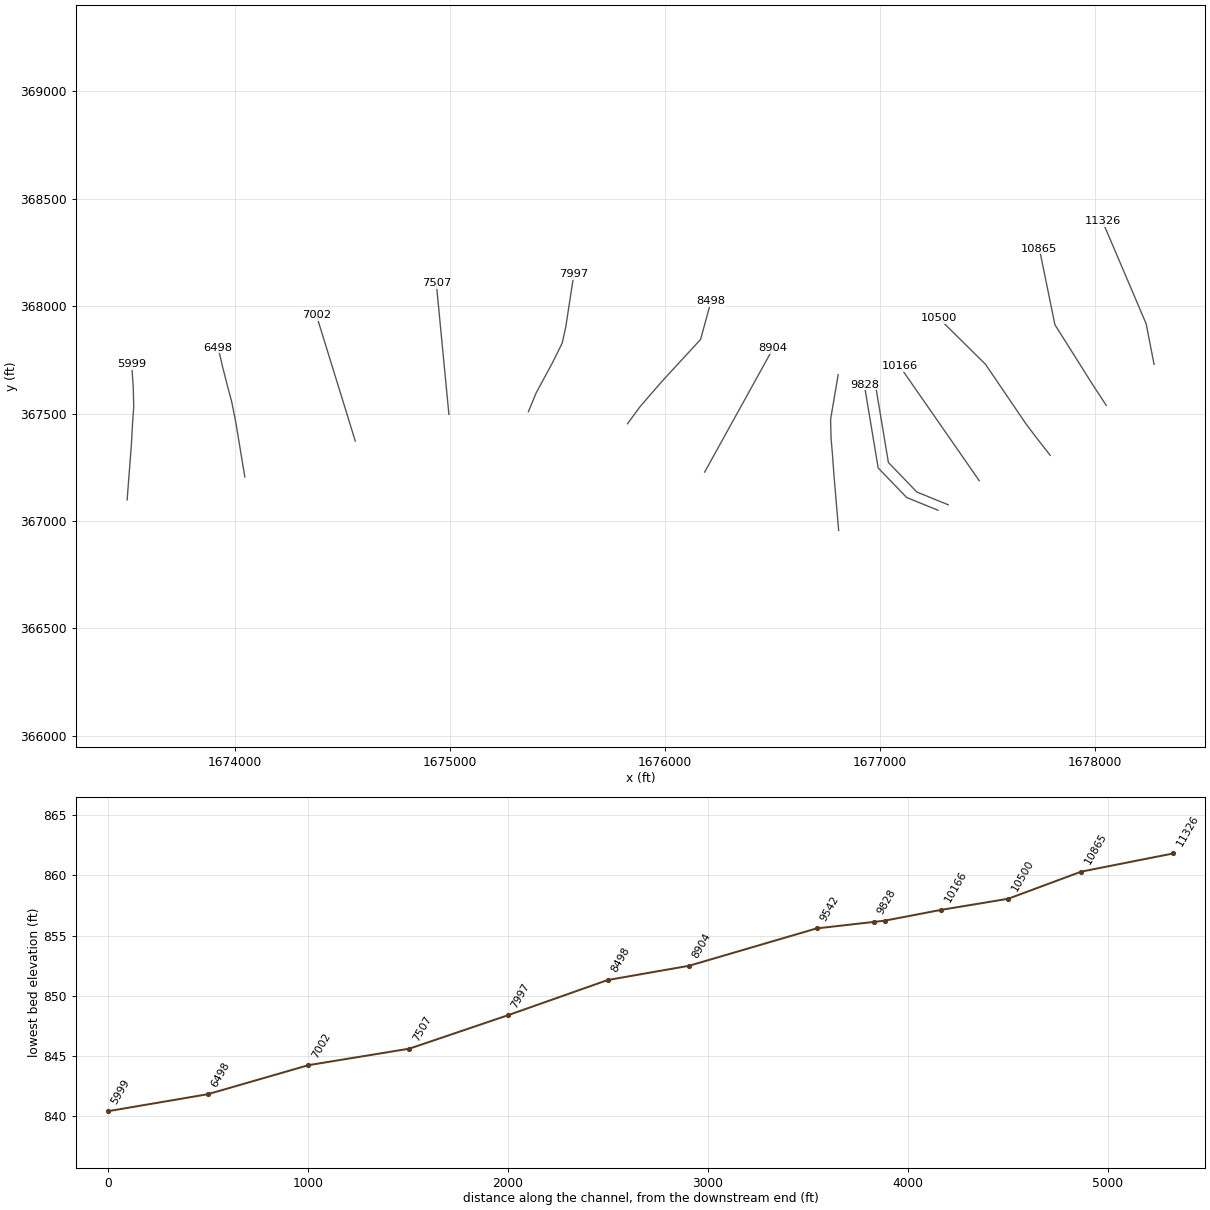
HEC-RAS study PRICERN.prj: PRICERN

--- PRICERN.g01 (geometry) --- (continued)

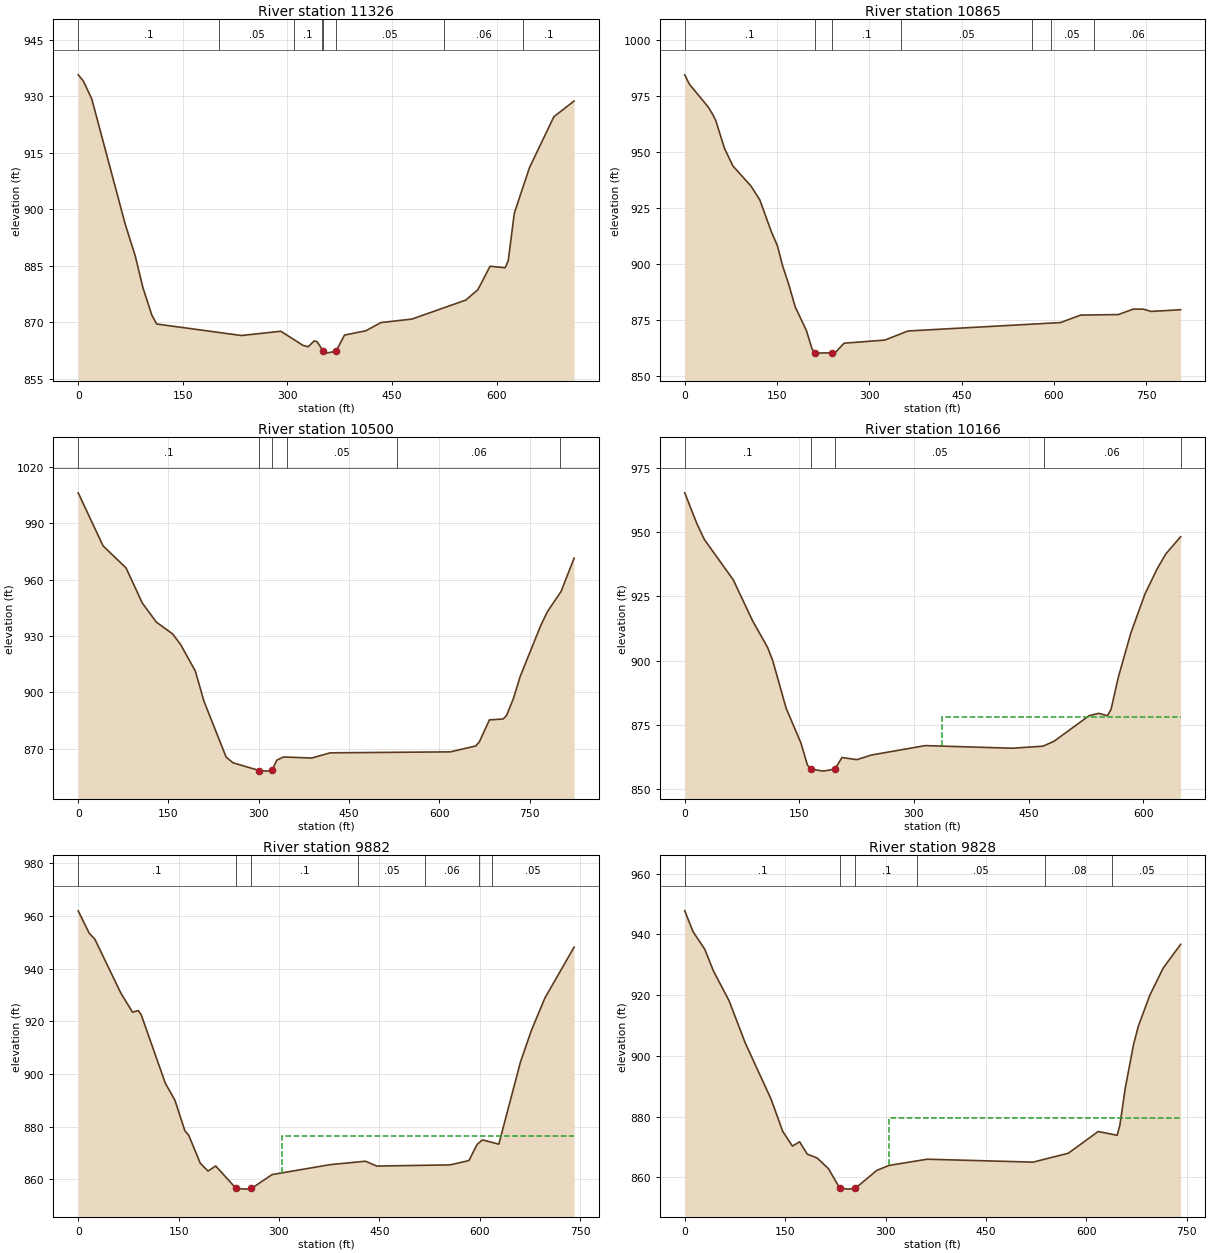
Type RM Length L Ch R = 1 ,11326   ,459.8,460.7,458.3
XS GIS Cut Line= 6
1678276.97889289367729.4015338451678240.24176163367918.121242227
1678205.95377246367998.6230497381678107.98808914368228.629151406
1678073.70009997 368309.131286981678036.96264064368395.383411066
#Sta/Elev= 30
       0  935.73     7.3  934.12    19.5   929.3    67.3  896.13    81.9  887.54
    92.8   879.2   105.7  871.86   112.6  869.54     234  866.49   290.5  867.62
   322.3  863.88   329.7   863.5   338.4  865.06   342.7   864.8   351.4  862.36
   355.8  861.81   369.7 862.321   381.8   866.6   412.3  867.74     434  869.93
   478.4  870.85   555.7   875.9   573.1  878.67   590.5  884.88   612.3  884.49
   616.6  886.42   625.3  898.98   647.1  911.11     682   924.6     711  928.78
#Mann= 8 ,-1,0
       0      .1       0  202.26     .05       0  309.76      .1       0
  349.76     .05       0   351.4    .045       0   369.7     .05       0
  524.76     .06       0  637.26      .1       0
Bank Sta=351.4,369.7
XS Rating Curve= 0 ,0
Exp/Cntr(USF)=0,0
Exp/Cntr=0.3,0.1

Type RM Length L Ch R = 1 ,10865   ,365.4,365.2,365.7
XS GIS Cut Line= 4
1678054.33267758367538.3596298661677987.88869357367640.305644232
1677815.68688734367913.7766097491677743.30625592368267.645958854
#Sta/Elev= 30
       0   984.5     7.4  980.39    37.9  970.24    45.6   966.8    50.3   964.2
    64.7  951.62    78.3  943.85   107.6   934.9     122  928.73   140.9  914.41
   150.7  908.23   158.8  899.56   169.2  890.82   179.7  880.86   197.6  870.52
     207  862.15   212.5   860.4   216.5   860.3   238.8860.4617   244.9  860.57
     259  864.74   325.2  866.12     363  870.18     611  873.94   643.4  877.27
   704.9  877.51   729.4  879.97   745.7  879.92     758  878.91   806.1  879.67
#Mann= 7 ,-1,0
       0      .1       0   212.5    .045       0   238.8      .1       0
  351.69     .05       0  564.86     .06       0  594.86     .05       0
  664.86     .06       0
Bank Sta=212.5,238.8
XS Rating Curve= 0 ,0
Exp/Cntr(USF)=0,0
Exp/Cntr=0.3,0.1

Type RM Length L Ch R = 1 ,10500   ,335.4,334.4,334
XS GIS Cut Line= 6
1677793.57767959367305.933337256 1677735.1092926367380.690733671
1677682.18682626367450.5196622611677640.04681867 367512.56153293
1677492.55269109367729.706111759 1677276.3939141367943.493104876
#Sta/Elev= 30
       0 1006.21    41.3  977.97    79.5  966.25   106.5  947.55   129.8  937.39
   156.9   931.1     170  925.54   194.6  911.34   209.1  895.16   245.9  865.46
   257.5  862.46     301  858.36   314.4  858.05   321.8  858.43     330   863.9
     341  865.58   388.1  865.03   418.7  867.79   618.5  868.31   660.6  871.45
   666.6  873.65   683.3  885.33   706.2  885.82   711.8  887.68   723.2  896.72
   734.4  908.43   768.6   935.6   779.7  942.96   802.4  953.71     824  971.44
#Mann= 6 ,-1,0
       0      .1       0     301    .045       0   321.8      .1       0
  347.52     .05       0  530.02     .06       0  800.02      .1       0
Bank Sta=301,321.8
XS Rating Curve= 0 ,0
Exp/Cntr(USF)=0,0
Exp/Cntr=0.3,0.1

Type RM Length L Ch R = 1 ,10166   ,283.5,283.9,286
XS GIS Cut Line= 2
1677463.63178819367187.5203171041677093.53284651367720.598609244
#Sta/Elev= 30
       0  965.19    15.8  953.32    25.6  947.11    63.6  931.36    88.9  915.44
   108.4  905.19   115.3  899.89   132.7  881.57   152.2  867.97   160.5  859.53
   165.2   857.9   181.4  857.13   196.6857.9291   205.8  862.42   225.2  861.58
   244.7  863.41   314.8  867.04   428.6  866.02   468.9  866.82   483.3  868.72
   529.2  878.64   541.8  879.57   553.3  878.64     558  881.16   567.3  893.41
   583.8  910.69   602.3   925.9   618.3  935.67   629.4  941.38     649  948.15
#Mann= 5 ,-1,0
       0      .1       0   165.2    .045       0   196.6     .05       0
     470     .06       0  648.96      .1       0
#XS Ineff= 1 ,-1
  336.12648.9574  878.09
Permanent Ineff=
       F
Bank Sta=165.2,196.6
XS Rating Curve= 0 ,0
Exp/Cntr(USF)=0,0
Exp/Cntr=0.3,0.1

Type RM Length L Ch R = 1 ,9882    ,52.9,53.2,53
XS GIS Cut Line= 4
1677319.32715497367075.4720136611677173.32482018367134.891568517
1677040.90409793 367272.405395471676976.39143837 367659.48135282
#Sta/Elev= 30
       0  961.95    16.4  953.47    24.8   951.2    63.9   930.6    81.2  923.45
    89.8  924.07    94.2  922.42   130.2  896.45   144.5  890.02   159.4  878.42
   165.1  876.71   182.4  866.07     194   863.1   205.5  865.02     236  856.48
   251.6  856.23   258.7  856.47   289.8  861.76   376.9  865.55   429.3  866.83
     446     865   555.5  865.43   583.9  867.08     596   873.2   604.1  874.94
   628.5  873.31   660.9  904.54   677.1  916.47   697.4  928.83     741  948.16
#Mann= 7 ,-1,0
       0      .1       0     236    .045       0   258.7      .1       0
  418.54     .05       0  518.54     .06       0  598.54     .08       0
  618.54     .05       0
#XS Ineff= 1 ,-1
  303.96740.9522  876.54
Permanent Ineff=
       F
Bank Sta=236,258.7
XS Rating Curve= 0 ,0
Exp/Cntr(USF)=0,0
Exp/Cntr=0.3,0.1

Type RM Length L Ch R = 1 ,9828    ,292,286.2,275.2
XS GIS Cut Line= 4
1677271.79151108367050.0064901511677125.78917629367109.426045007
1676993.36845404 367246.939871961676928.85579448 367634.01582931
#Sta/Elev= 30
       0  947.76    12.6  940.83    29.9  935.13    42.8  928.01    66.2  918.18
    90.3  904.33   129.2  885.67   146.5   875.1     161  870.29   171.6  871.73
   183.1  867.65   197.8  866.39   214.8  862.88   231.7  856.41   245.2  856.13
   254.8  856.39   286.9  862.28   305.3  863.94   362.3  865.98   520.5  865.02
   573.2  867.95   617.8   875.1   646.2  873.86   650.2  877.18   658.3  889.43
   670.5  903.57   677.7   909.7   694.8  919.89   715.1  928.97     741  936.73
#Mann= 6 ,-1,0
       0      .1       0   231.7    .045       0   254.8      .1       0
  347.63     .05       0  538.54     .08       0  638.54     .05       0
#XS Ineff= 1 ,-1
  305.73740.9522  879.71
Permanent Ineff=
       F
Bank Sta=231.7,254.8
XS Rating Curve= 0 ,0
Exp/Cntr(USF)=0,0
Exp/Cntr=0.3,0.1

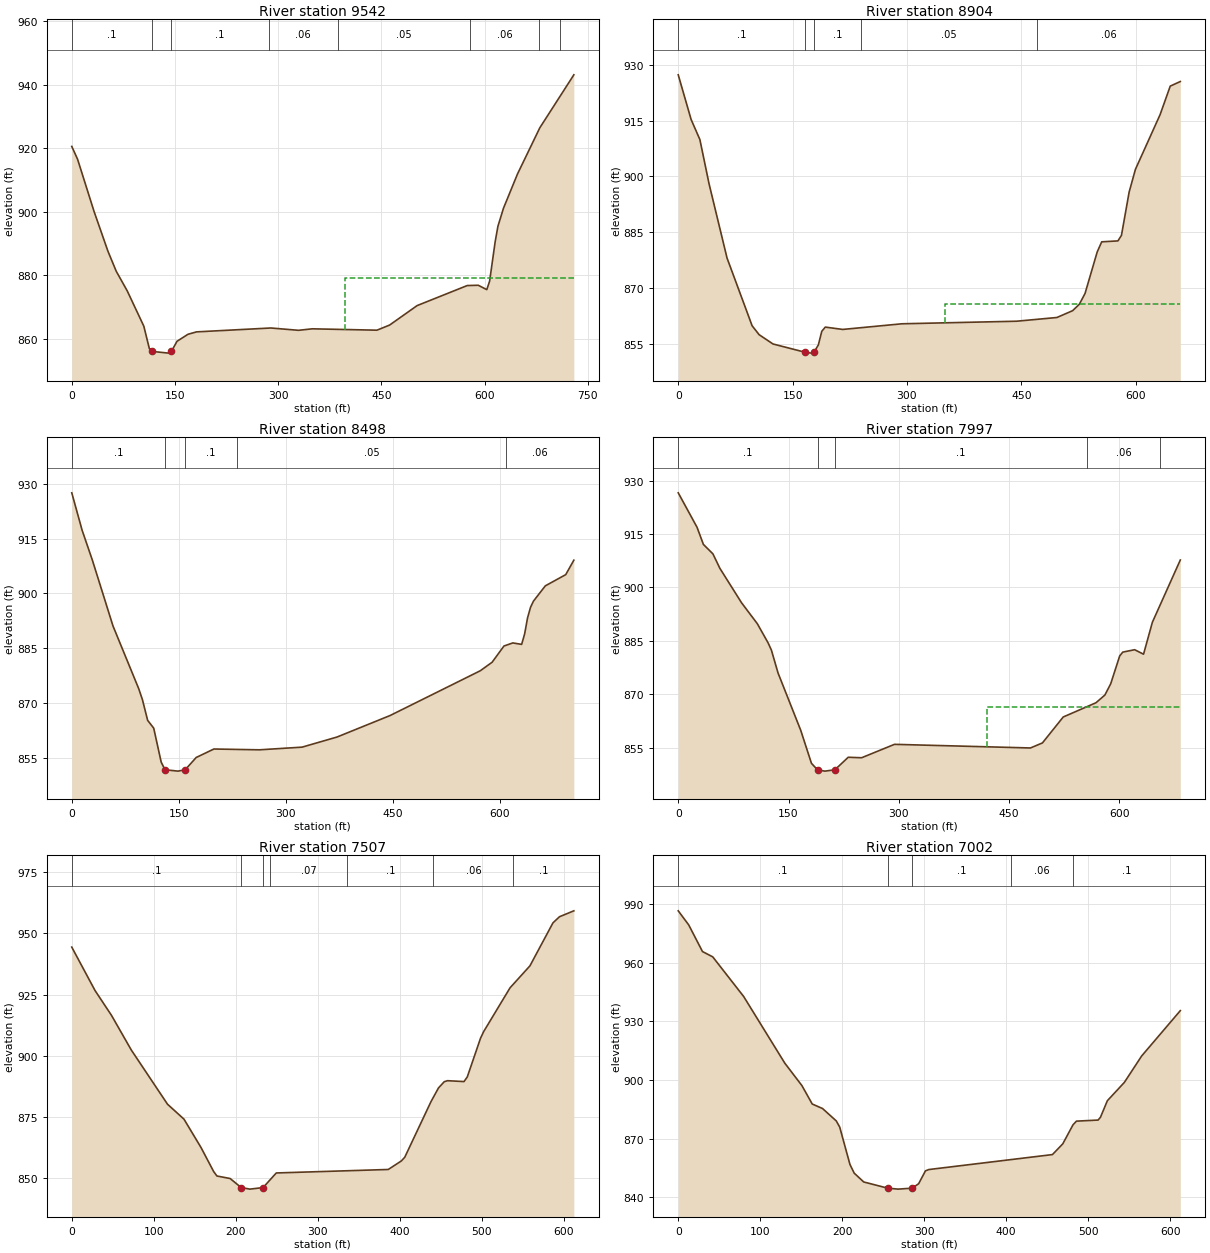
Type RM Length L Ch R = 1 ,9542    ,643,638.2,625
XS GIS Cut Line= 6
1676809.39041294 366956.208734511676787.65456404367211.574693603
1676780.48233429367311.3179324241676773.98759662367386.032349926
1676771.90164278367473.5997600971676807.17801992367681.212746582
#Sta/Elev= 30
       0  920.56     8.4  916.56    32.4  900.11    52.5  887.66    64.6  881.33
    80.6  875.15   104.7  864.06   112.7  857.03   115.9856.1473   140.8  855.59
   144.9  856.17   152.9  859.31   168.9  861.52   181.3  862.27   289.3  863.49
   329.4  862.76   349.5  863.23   443.4   862.8   461.8  864.41   501.8  870.53
   574.6  876.83   590.6  876.92     603  875.55   607.1  878.18   615.2  890.62
   619.2  895.47   627.3  901.15   647.6  911.88   680.1  926.43   729.5  943.06
#Mann= 8 ,-1,0
       0      .1       0   115.9    .045       0   144.9      .1       0
  286.29     .06       0  386.29     .05       0  578.88     .06       0
  678.88      .1       0  708.88     .05       0
#XS Ineff= 2 , 0
                          397.36          879.26
Permanent Ineff=
       F       F
Bank Sta=115.9,144.9
XS Rating Curve= 0 ,0
Exp/Cntr(USF)=0,0
Exp/Cntr=0.3,0.1

Type RM Length L Ch R = 1 ,8904    ,410.1,406.2,403.9
XS GIS Cut Line= 2
1676185.99280948367227.7085461451676504.57384433367804.088707891
#Sta/Elev= 30
       0  927.33    16.9  915.32    28.4  909.92    40.4  898.06      64  878.08
    96.9  859.86   106.1  857.45   124.3  854.95   166.6852.7173   174.6  852.49
     178  852.72   183.8  854.69   188.3  858.36   192.9  859.49   215.8  858.86
   293.4  860.38   443.7  861.07   496.7  862.07   517.3   863.9   526.1  865.62
   533.6  868.52   549.6  879.71   555.5  882.42   576.8  882.67   581.4  884.17
   591.5  895.82   599.7   901.9   632.1  916.63   645.4  924.29   658.6  925.53
#Mann= 5 ,-1,0
       0      .1       0   166.6    .045       0     178      .1       0
     240     .05       0     470     .06       0
#XS Ineff= 1 ,-1
     350658.5651  865.59
Permanent Ineff=
       F
Bank Sta=166.6,178
XS Rating Curve= 0 ,0
Exp/Cntr(USF)=0,0
Exp/Cntr=0.3,0.1

Type RM Length L Ch R = 1 ,8498    ,492,500.4,499.5
XS GIS Cut Line= 6
1675826.96929128367452.8345694081675882.70310369367528.953839748
1675939.70889519367595.4071189151675989.00833727367651.964420496
1676166.80292919 367845.084441081676215.62933866368023.044008598
#Sta/Elev= 30
       0  927.57    14.5  917.33      29  909.06    57.8  891.09    93.8  873.94
    99.1  870.89   106.4  865.22   114.9  863.09   125.4  853.77   130.7  851.69
   148.9  851.31   158.9 851.665   174.5  855.05   199.3  857.37   263.1  857.15
   322.9  857.88   371.9  860.65   446.4  866.55   572.8  878.81   589.4  881.15
     606  885.59   618.4  886.44   630.8  886.04     635  888.91   639.1  893.31
   643.3  896.22   647.4   897.9     664  902.08   692.6  905.15     704  909.11
#Mann= 5 ,-1,0
       0      .1       0   130.7    .045       0   158.9      .1       0
   231.9     .05       0  609.42     .06       0
Bank Sta=130.7,158.9
XS Rating Curve= 0 ,0
Exp/Cntr(USF)=0,0
Exp/Cntr=0.3,0.1

Type RM Length L Ch R = 1 ,7997    ,484.8,490.6,498.8
XS GIS Cut Line= 6
1675365.82122837367508.8887940031675401.65186538367595.814801259
1675478.82756405367738.8191084251675523.18574304367828.513154758
1675539.95703496367904.6166770891675577.53452506368150.076214204
#Sta/Elev= 30
       0  926.61    25.6  916.92    34.2  912.12    47.2  909.44    56.6   905.4
    86.1  895.71   107.6  889.81   122.1  884.48   126.7   882.4   135.7  875.99
   166.6  859.85   181.2  850.57   189.5848.7267   199.4  848.38     213  848.75
   231.2  852.28   249.4  852.14   294.1  855.91     479  854.89   495.3  856.31
   523.6   863.6   568.1   867.6   580.2  869.76   588.1  872.91   600.4  880.78
   604.5  881.83   620.7  882.51   632.8  881.25   644.8  890.22   682.8  907.73
#Mann= 5 ,-1,0
       0      .1       0   189.5    .045       0     213      .1       0
  555.82     .06       0  655.82      .1       0
#XS Ineff= 2 , 0
                          420.15          866.47
Permanent Ineff=
       F       F
Bank Sta=189.5,213
XS Rating Curve= 0 ,0
Exp/Cntr(USF)=0,0
Exp/Cntr=0.3,0.1

Type RM Length L Ch R = 1 ,7507    ,501.7,504.7,507.5
XS GIS Cut Line= 6
1674996.01909994367496.2424860881674987.04569269367589.562181337
1674978.67070944367676.6604323371674954.74162344367925.512624918
1674946.36696828368012.6108759181674937.39388911368105.930571167
#Sta/Elev= 30
       0  944.41    28.4  926.68    48.5  916.53    72.6  902.42   116.8  880.28
   136.9  874.18   157.8  862.54   173.1  852.79   177.1  850.98   193.2  849.95
   206.7846.2565   217.3  845.62   233.4  846.26   249.5  852.22   386.1  853.64
   402.1  857.14   406.2  858.61   438.3  881.39   447.4  886.93   454.4  889.47
   458.4  889.88   478.5  889.52   482.5  891.41   498.6  907.16   502.4  909.88
   534.7  927.81   558.9  936.74     587  954.29     595  956.81   612.5  959.22
#Mann= 7 ,-1,0
       0      .1       0   206.7    .045       0   233.4      .1       0
  241.25     .07       0  336.25      .1       0  441.25     .06       0
  538.75      .1       0
Bank Sta=206.7,233.4
XS Rating Curve= 0 ,0
Exp/Cntr(USF)=0,0
Exp/Cntr=0.3,0.1

Type RM Length L Ch R = 1 ,7002    ,504.7,503.7,501.6
XS GIS Cut Line= 6
1674560.17638213367372.2575031911674532.70137146367461.891510273
1674506.89597688367545.4996107761674484.77758279367617.163837532
1674455.28584387367712.7161398621674379.71414463367957.568996603
#Sta/Elev= 30
       0  986.42    12.8  979.22    29.6  965.61    42.1   962.9    79.8  942.67
     130  908.61   150.9  897.13   163.5  887.72   176.1  885.41   192.8  879.09
     197  875.95   209.5  856.84   214.7   852.4   226.3  847.91   255.3844.7664
   268.2  844.25   285.6  844.75   293.3  847.03   301.6  853.59   305.8  854.26
   456.5   861.9   469.1  867.37   481.6  877.11   485.8  878.98   512.2  879.53
   515.1  880.97   523.5  889.41   544.2  898.75   565.4   912.3   612.5  935.43
#Mann= 5 ,-1,0
       0      .1       0   255.3    .045       0   285.6      .1       0
  406.25     .06       0  481.25      .1       0
Bank Sta=255.3,285.6
XS Rating Curve= 0 ,0
Exp/Cntr(USF)=0,0
Exp/Cntr=0.3,0.1

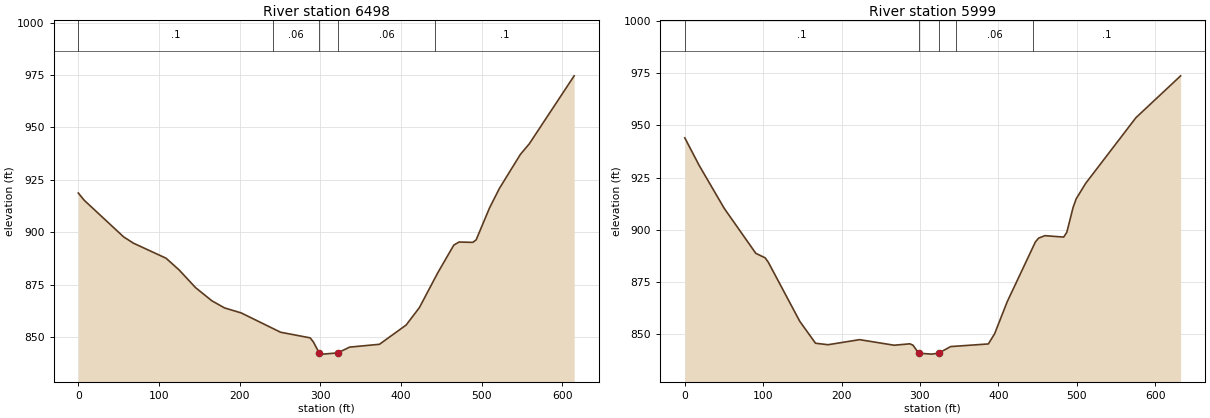
Type RM Length L Ch R = 1 ,6498    ,500.8,499.5,493.6
XS GIS Cut Line= 6
1674046.40604009367205.202567592  1674004.685323367457.904161915
1673985.10334118367556.1519969251673965.59156917367629.267664343
1673943.67461826 367714.800629751673922.44008067367806.859828845
#Sta/Elev= 30
       0   918.7     7.4  915.21    56.1   897.8    68.2   894.8   108.8  887.59
     125  881.99   145.3  873.58   165.5   867.3   181.2   863.9     202  861.49
   250.7  852.29   287.4   849.6   291.4  847.65   298.5842.4867   303.7  841.84
   321.7842.4471   336.3  845.18   373.3  846.53   406.4  855.72   422.8  864.02
   445.7  880.71   465.5  893.87     472  895.32     489  895.16   493.2  896.36
   509.7  911.53   522.1  920.96     548  937.11     559  942.14   614.7  974.62
#Mann= 5 ,-1,0
       0      .1       0  241.16     .06       0   298.5    .045       0
   321.7     .06       0  441.98      .1       0
Bank Sta=298.5,321.7
XS Rating Curve= 0 ,0
Exp/Cntr(USF)=0,0
Exp/Cntr=0.3,0.1

Type RM Length L Ch R = 1 ,5999    ,353.1,352.5,350.5
XS GIS Cut Line= 6
1673498.84873626367098.2418235091673518.50486493 367353.73671934
1673523.91167825367453.616440833 1673529.5937535367530.932231084
1673527.12328601367626.8503463421673519.93169934 367729.48301509
#Sta/Elev= 30
       0  944.07    18.3  930.89    50.4  910.23    90.6  888.73   102.6  886.56
   106.6  884.43   146.7  856.15   166.8  845.65   182.8  844.94     223  847.37
   267.1  844.69   287.1  845.37   291.1  844.73   298.4  840.87   315.1  840.43
   323.8840.8798   339.2  844.05   387.3  845.31   395.3  850.21   411.3   865.5
   447.4  894.26   451.4  896.01   459.4   897.2   483.4  896.52   487.4   898.8
   495.4  910.73   499.4  914.88   511.4  922.24   575.5   953.7   632.6  973.79
#Mann= 5 ,-1,0
       0      .1       0   298.4    .045       0   323.8      .1       0
  346.25     .06       0   443.8      .1       0
Bank Sta=298.4,323.8
XS Rating Curve= 0 ,0
Exp/Cntr(USF)=0,0
Exp/Cntr=0.3,0.1