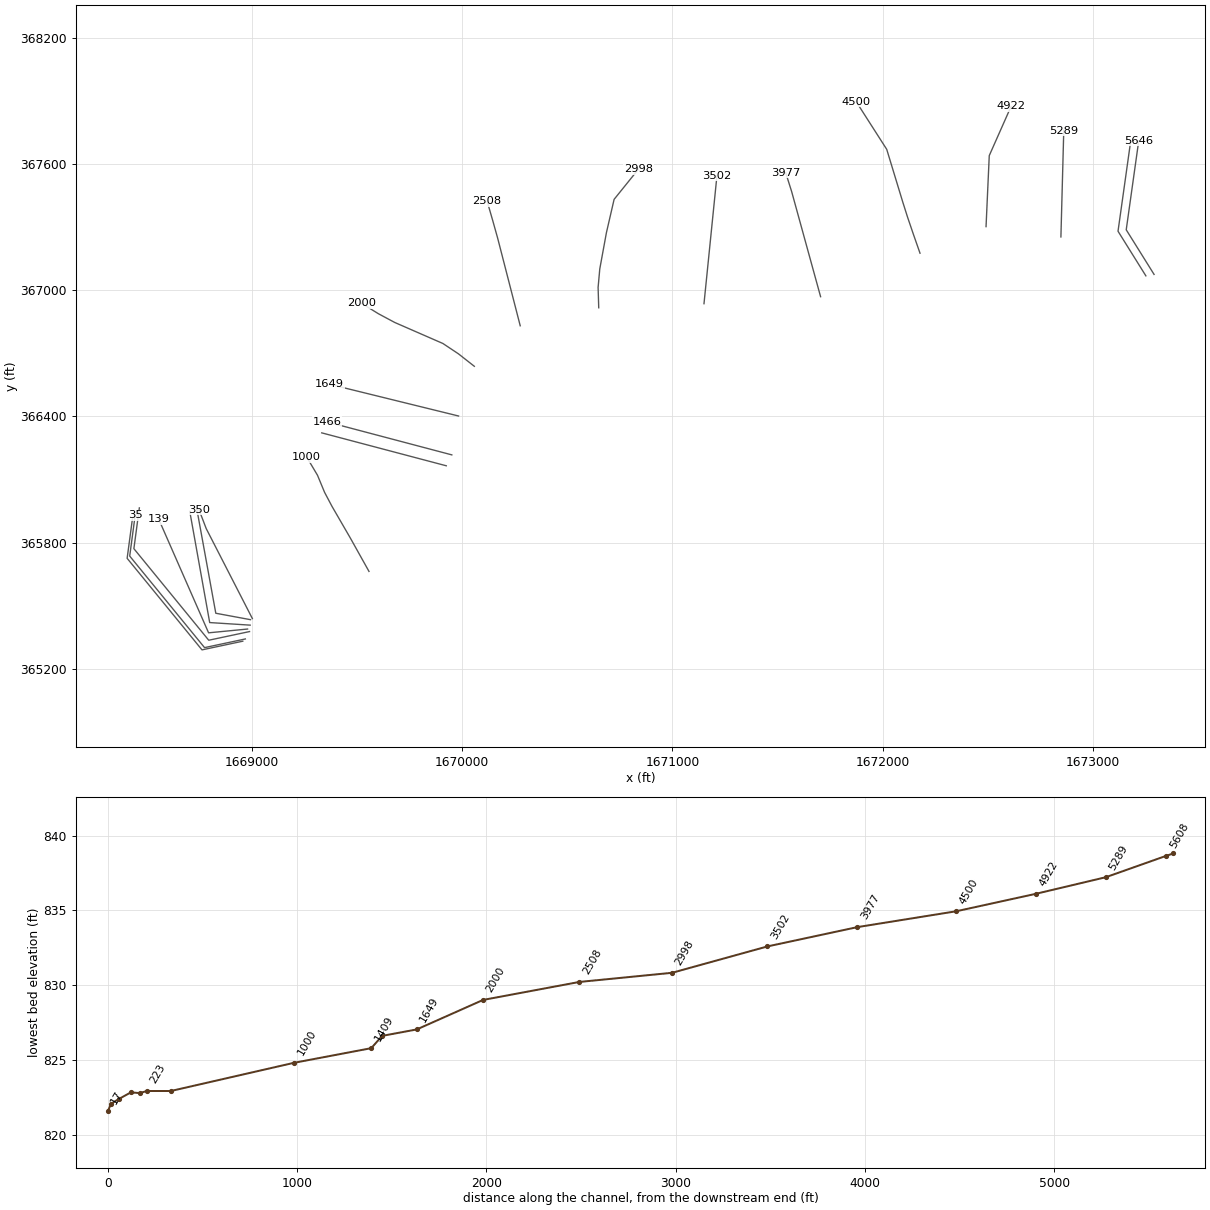
HEC-RAS study PRICERN.prj: PRICERN

--- PRICERN.g01 (geometry) --- (continued)

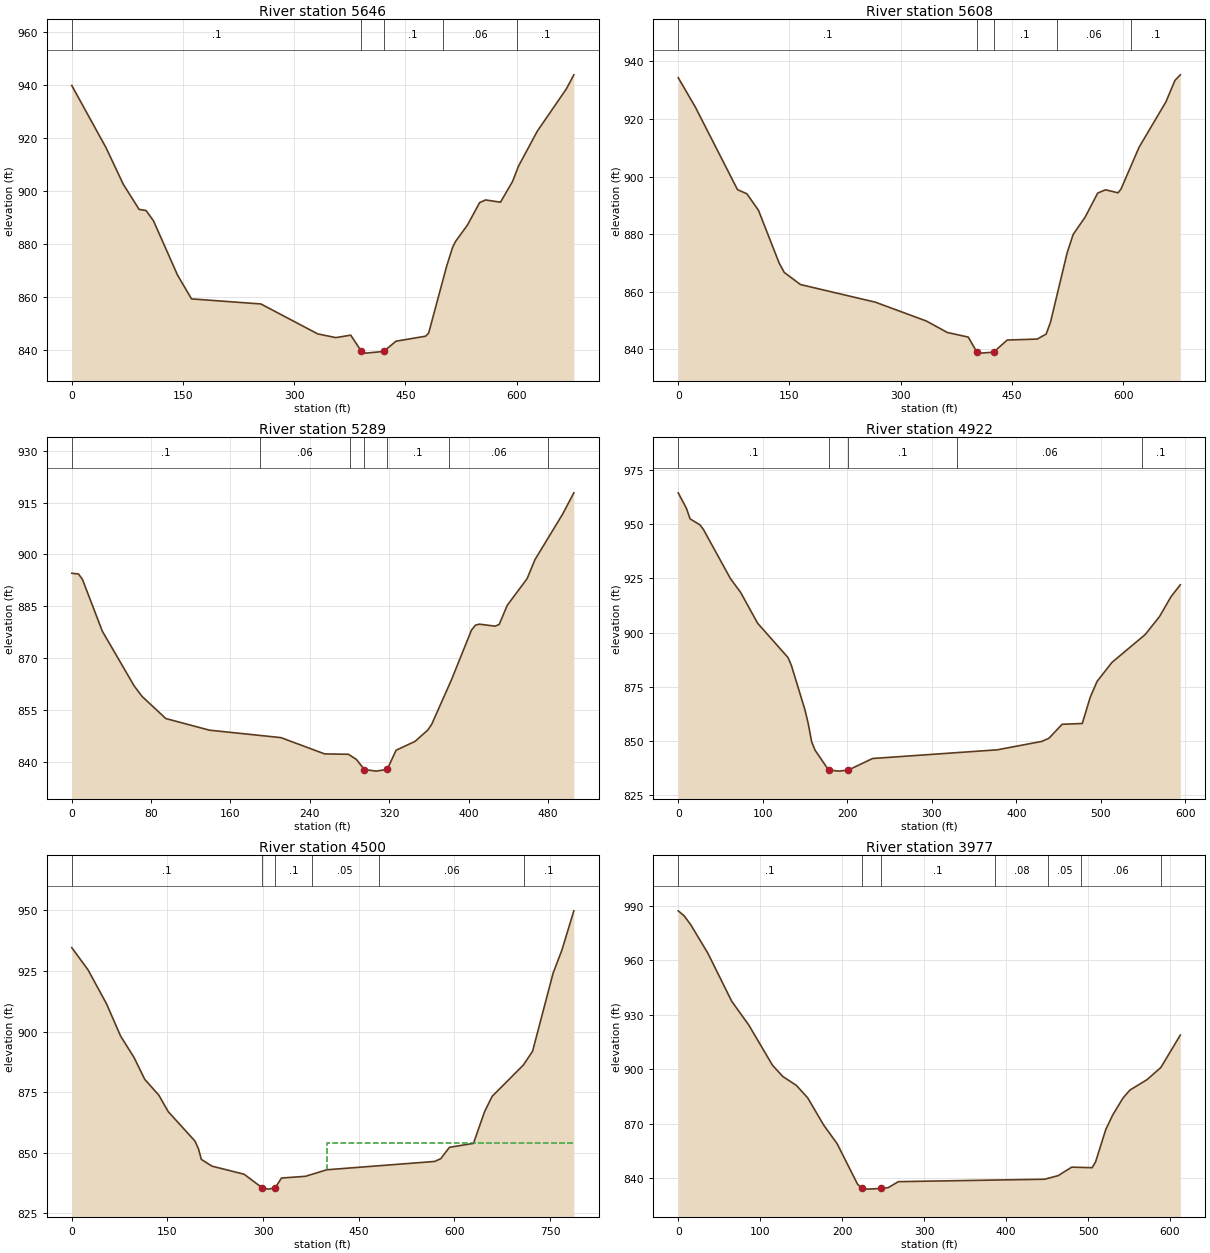
Type RM Length L Ch R = 1 ,5646    ,37.7,37.9,38.5
XS GIS Cut Line= 3
1673290.87100424  367075.50927461673158.45028199367287.721970516
1673217.86983684 367710.44966078
#Sta/Elev= 30
       0  939.74    46.3  916.22    69.5  902.47    90.8  893.01   100.2  892.58
   110.2  888.71   142.7  868.19   161.5  859.26     255  857.35   331.7  846.06
     356  844.66   376.2  845.59   390.5  839.49   396.4  838.81   420.6  839.45
   437.1   843.3   477.2   845.2   481.2  846.35   505.4   871.5   513.5   878.7
   517.6  880.97   533.7  887.17   549.9  895.55     558  896.57   578.1  895.72
   594.3  903.52   602.4  909.33   627.7  922.49     667  938.49     677  943.75
#Mann= 5 ,-1,0
       0      .1       0   390.5    .045       0   420.6      .1       0
  500.14     .06       0  600.14      .1       0
Bank Sta=390.5,420.6
XS Rating Curve= 0 ,0
Exp/Cntr(USF)=0,0
Exp/Cntr=0.3,0.1

Type RM Length L Ch R = 1 ,5608    ,317.6,319.5,320.3
XS GIS Cut Line= 3
1673251.82386819367068.7184683311673119.40314594367280.931164247
 1673178.8227008367703.658854511
#Sta/Elev= 30
       0  934.35    23.4  923.98    79.9  895.46    92.6     894   108.2  888.28
   136.1  869.93     143  866.68   164.8  862.48   265.9  856.34   334.6   849.8
   362.8  845.83   391.1  844.22   402.7  838.98   407.3  838.65   425.2838.9759
   443.6   843.2     484  843.53   496.1  845.27   501.9  849.34   524.4  873.49
   532.5  879.87   548.7  885.92   565.6  894.26   576.2  895.39   593.1  894.35
   597.1  895.69   621.4  910.18   657.7  925.99   669.8  933.41     677  935.34
#Mann= 5 ,-1,0
       0      .1       0   402.7    .045       0   425.2      .1       0
  510.14     .06       0  610.14      .1       0
Bank Sta=402.7,425.2
XS Rating Curve= 0 ,0
Exp/Cntr(USF)=0,0
Exp/Cntr=0.3,0.1

Type RM Length L Ch R = 1 ,5289    ,367,366.8,366.5
XS GIS Cut Line= 2
1672847.77089517 367253.767939171672861.35250771367759.683006232
#Sta/Elev= 30
       0  894.53     6.8  894.33    10.8  892.73    30.8  877.76    62.8  861.95
    70.8  858.88    94.8  852.45   138.8  849.08   210.8  846.93   254.9  842.21
   278.9   842.1   286.9  840.61   294.9  837.69   306.9  837.22     318837.7287
   326.9  843.27     346  845.83   358.9  849.13   362.9  850.84   382.9  863.78
   402.9  878.06   406.9   879.5   410.9  879.79   426.9  879.21   430.9  879.73
   438.9  885.22     459  892.98   466.9  898.47   494.9  911.72   506.1  917.83
#Mann= 7 ,-1,0
       0      .1       0     190     .06       0     280      .1       0
   294.9    .045       0     318      .1       0     380     .06       0
     480      .1       0
Bank Sta=294.9,318
XS Rating Curve= 0 ,0
Exp/Cntr(USF)=0,0
Exp/Cntr=0.3,0.1

Type RM Length L Ch R = 1 ,4922    ,419.2,422.2,426.3
XS GIS Cut Line= 3
1672491.69312868367302.7779285761672506.99340206367640.641499753
1672610.74183118367874.547049029
#Sta/Elev= 30
       0   964.4     9.8  957.16      14  952.42    25.8  949.61    29.8  947.52
    61.8  924.86    73.8  918.53    93.9  904.32   129.9  888.47   133.9  884.86
   149.9  864.43   153.9  857.92   157.9  849.62   161.9  845.78   177.9  836.64
   190.1  836.12   201.3  836.62     230  841.94   377.5  845.94   430.2  849.82
   438.7  851.29   454.2   857.7   478.1  858.08   487.5  870.16   495.6  877.47
   513.1  886.19   552.5  899.06   569.4  907.31   583.1  916.53   594.1  922.02
#Mann= 5 ,-1,0
       0      .1       0   177.9    .045       0   201.3      .1       0
     330     .06       0  548.21      .1       0
Bank Sta=177.9,201.3
XS Rating Curve= 0 ,0
Exp/Cntr(USF)=0,0
Exp/Cntr=0.3,0.1

Type RM Length L Ch R = 1 ,4500    ,524.6,523.1,522.9
XS GIS Cut Line= 6
1672177.62926584367176.3778220861672146.62735935367264.938012421
1672118.39874126367347.8095658421672095.71637192367419.302861169
1672019.28673476367670.4296555071671874.61824122 367896.35310729
#Sta/Elev= 30
       0  934.64    25.6  925.45    54.7  911.34    76.5  898.17    97.6  889.32
   114.5  880.24   136.5  873.75   151.2  866.95   193.3  854.74   198.9  851.41
   203.1  847.23   219.9  844.43   270.2   841.1   298.7  835.48   308.3  834.95
   318.9  835.46   328.8  839.53   366.4  840.24   399.8  842.94     569  846.38
   578.4   847.5   592.2  852.21   629.8  853.84   647.2  866.89   659.1  873.26
     708  886.16   722.5  891.87   754.7  924.13   768.4  933.57   787.2  949.84
#Mann= 6 ,-1,0
       0      .1       0   298.7    .045       0   318.9      .1       0
  376.38     .05       0  481.38     .06       0  708.88      .1       0
#XS Ineff= 2 , 0
                             400          853.97
Permanent Ineff=
       F       F
Bank Sta=298.7,318.9
XS Rating Curve= 0 ,0
Exp/Cntr(USF)=0,0
Exp/Cntr=0.3,0.1

Type RM Length L Ch R = 1 ,3977    ,480.4,475.4,470.1
XS GIS Cut Line= 6
1671704.74257597366969.6209423451671636.71384064 367216.67589443
1671610.16566538367313.0877751021671590.25527215367385.396357512
1671567.02565981367469.7564250141671538.78391839367559.219172603
#Sta/Elev= 30
       0  987.22     7.2  984.48    15.5  979.39    36.2  963.84    65.3  937.36
      86  924.35     115  902.16   127.5  895.97   144.1  891.06   157.9  884.24
   177.3   869.3   193.9  858.89   218.8  836.61   224.5834.2468   231.2  833.89
   247.8  834.25   256.1  834.69   268.6  838.01     447  839.34   463.5  841.31
   480.1     846     505   845.7   509.2  848.87   521.7  866.78   530.1  874.71
   542.6  884.03     551  888.42     572  894.21   588.8  900.88   612.6  918.74
#Mann= 7 ,-1,0
       0      .1       0   224.5    .045       0   247.8      .1       0
  386.25     .08       0  451.25     .05       0  491.25     .06       0
  588.75      .1       0
Bank Sta=224.5,247.8
XS Rating Curve= 0 ,0
Exp/Cntr(USF)=0,0
Exp/Cntr=0.3,0.1

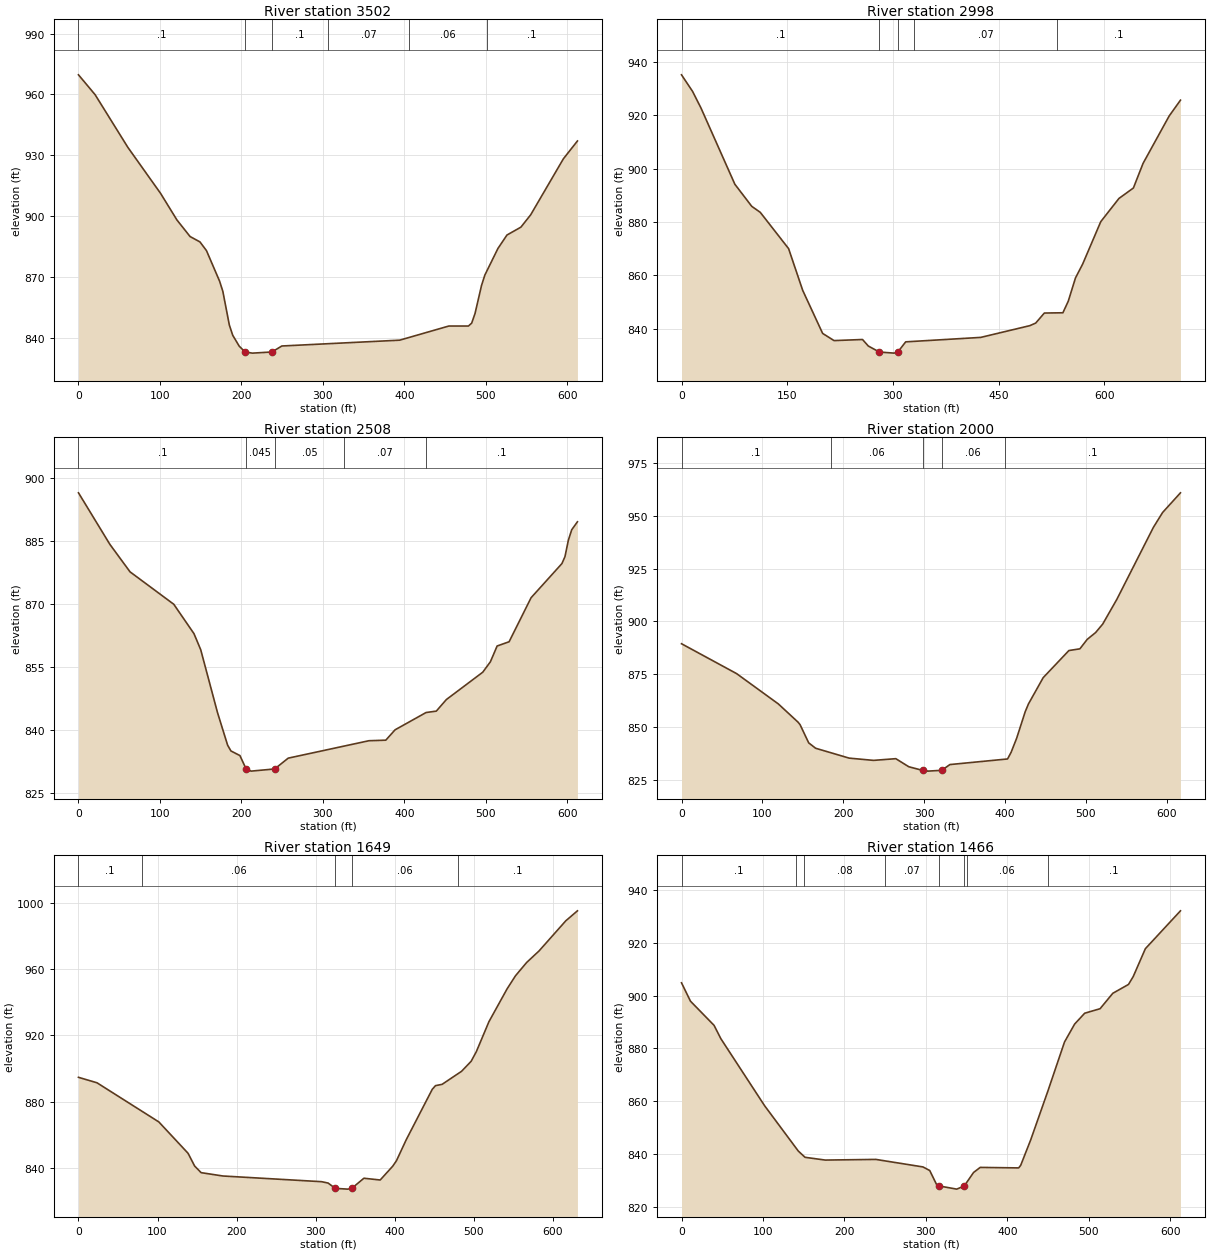
Type RM Length L Ch R = 1 ,3502    ,505,503.8,502.5
XS GIS Cut Line= 6
1671150.13415166366936.2461620381671159.58787292367029.520581792
1671175.97399499367191.2046416211671186.02417175367290.698209043
1671202.40799724367452.3579907081671211.86139041367545.628145377
#Sta/Elev= 30
       0  969.65    20.4  959.88    60.6  933.94   100.8  911.25   120.9  898.15
     137  890.01   149.1  887.37   157.1  883.09   173.2  868.05   177.2  863.04
   185.2  846.41   189.3  841.43   197.3  836.04   204.5  833.16   213.4   832.6
   237.5  833.16   249.6  836.11   394.3  838.98   454.6  845.94   478.7  845.94
   482.7  847.39   486.8  852.13   494.8  865.98   498.8     871   514.9  884.14
     526  890.76   543.1  894.64   555.1  900.71   595.3  928.33   612.5  937.07
#Mann= 6 ,-1,0
       0      .1       0   204.5    .045       0   237.5      .1       0
  306.26     .07       0  406.26     .06       0  501.26      .1       0
Bank Sta=204.5,237.5
XS Rating Curve= 0 ,0
Exp/Cntr(USF)=0,0
Exp/Cntr=0.3,0.1

Type RM Length L Ch R = 1 ,2998    ,483.1,489.4,493.4
XS GIS Cut Line= 6
1670649.47418568366916.843907847   1670646.54637367013.917860686
1670654.51584226367101.8894695181670686.10108092367274.199820428
1670722.64037792367432.5387426011670838.79167603367576.516389852
#Sta/Elev= 30
       0  935.26    15.7  929.04    27.7  922.77    75.7  894.22    99.7  885.91
   111.8  883.66     152  870.05     172   854.4   200.3  838.24   216.5  835.54
   256.9  835.95   265.1  833.51   280.8 831.252   301.8  830.84   306.8  831.19
   318.2  835.07   424.7  836.74   494.4  841.15   502.7  842.11     515  845.88
   541.3  845.98   548.9  850.29   559.2  859.06   569.4  864.27   595.1  880.18
   620.9  888.88   641.4   892.8   655.1  902.03   692.1  919.79   708.2  925.75
#Mann= 5 ,-1,0
       0      .1       0   280.8    .045       0   306.8      .1       0
  330.65     .07       0  533.18      .1       0
Bank Sta=280.8,306.8
XS Rating Curve= 0 ,0
Exp/Cntr(USF)=0,0
Exp/Cntr=0.3,0.1

Type RM Length L Ch R = 1 ,2508    ,497.4,508.4,521.6
XS GIS Cut Line= 6
1670276.10523497 366831.206544271670252.72109539366921.993436192
1670187.24419222367176.1960117711670168.53622438367248.825459693
1670144.91619288367333.0976008521670118.83061514367423.188299944
#Sta/Elev= 30
       0  896.51    38.5  884.25    63.3  877.69     117  869.97   141.8  862.97
   150.1  859.13   170.7  844.16   183.1  836.41   187.2  835.03   198.2  833.94
   205.8830.7531     212  830.23   240.9  830.75   257.5  833.32   356.6  837.47
   377.3   837.6   388.7  840.07   426.8  844.19   439.3  844.52   451.7  847.28
   496.3  853.78   505.7  856.26     514  860.03   528.7  861.04   555.7  871.53
   593.6  879.67   597.3  881.32   601.5  885.26   605.6  887.72   612.6  889.61
#Mann= 5 ,-1,0
       0      .1       0   205.8    .045       0   240.9     .05       0
  326.25     .07       0  426.25      .1       0
Bank Sta=205.8,240.9
XS Rating Curve= 0 ,0
Exp/Cntr(USF)=0,0
Exp/Cntr=0.3,0.1

Type RM Length L Ch R = 1 ,2000    ,348.5,350.5,352
XS GIS Cut Line= 6
1670057.80312492366638.4993046671669982.28785601366697.760341004
1669908.35854192366746.9626704161669679.22776659366846.958205342
1669601.81880067366888.3554322571669521.38490643 366938.12436159
#Sta/Elev= 30
       0  889.38    68.1  875.24   119.8  860.86   144.3  852.17   146.7  851.01
   157.3  842.43   165.9  839.87   207.4  835.19   237.5  834.12   265.1  834.93
   281.1  831.11   298.5  829.35   304.6  829.03   321.8  829.41     332  832.14
   403.3  834.79   407.7  837.94   414.6  844.65   425.1  857.12   429.2  860.89
   447.4  873.32   479.2  886.16   492.8  886.97   501.8  891.43   512.2  894.67
     521  898.69   538.5  910.41   583.7  944.51   595.1  951.56   617.2  960.88
#Mann= 5 ,-1,0
       0      .1       0   184.8     .06       0   298.5    .045       0
   321.8     .06       0   399.8      .1       0
Bank Sta=298.5,321.8
XS Rating Curve= 0 ,0
Exp/Cntr(USF)=0,0
Exp/Cntr=0.3,0.1

Type RM Length L Ch R = 1 ,1649    ,183.2,183,181.6
XS GIS Cut Line= 2
1669982.83347858366402.0480398591669369.77457927366552.954845843
#Sta/Elev= 30
       0  894.69    23.4  891.39   101.7   867.7   138.7  848.72     147  841.01
   155.2  837.02   182.8     835   307.6  831.56   315.9  830.73     325  827.51
   340.6  827.06   345.8827.5103   361.2  833.65   381.8  832.58   397.7  840.96
   402.4  844.26   414.7  856.89   447.7  887.44   451.8  889.66   460.1  890.43
   484.8  898.34   496.9  904.39   503.5  910.26   519.4  928.33   542.4  948.21
     553  956.11   567.2  964.19   582.8  971.12   616.6  989.33   631.4   995.4
#Mann= 5 ,-1,0
       0      .1       0      80     .06       0     325    .045       0
   345.8     .06       0     480      .1       0
Bank Sta=325,345.8
XS Rating Curve= 0 ,0
Exp/Cntr(USF)=0,0
Exp/Cntr=0.3,0.1

Type RM Length L Ch R = 1 ,1466    ,57.3,57.3,57.2
XS GIS Cut Line= 2
1669950.76578231366217.1872025281669358.45656882366373.753013736
#Sta/Elev= 30
       0  904.81      11  897.85      40  888.68    48.3  883.64     102  858.25
   143.4  841.06   151.7  838.69   176.5  837.64   238.6  837.89   296.5  835.04
   304.8  833.68     313  828.51   315.8  827.86   337.9  826.63   347.2827.8175
   358.6  832.93   366.8  834.86     414  834.67   416.5  835.64   428.9  845.38
     450  863.89   470.3  882.37   482.7  889.16   495.1  893.29     514     895
   529.6  900.84   548.9   904.2   554.7  907.19   569.6  917.74   612.7  932.09
#Mann= 8 ,-1,0
       0      .1       0     140     .07       0     150     .08       0
     250     .07       0   315.8    .045       0   347.2     .07       0
     350     .06       0     450      .1       0
Bank Sta=315.8,347.2
XS Rating Curve= 0 ,0
Exp/Cntr(USF)=0,0
Exp/Cntr=0.3,0.1

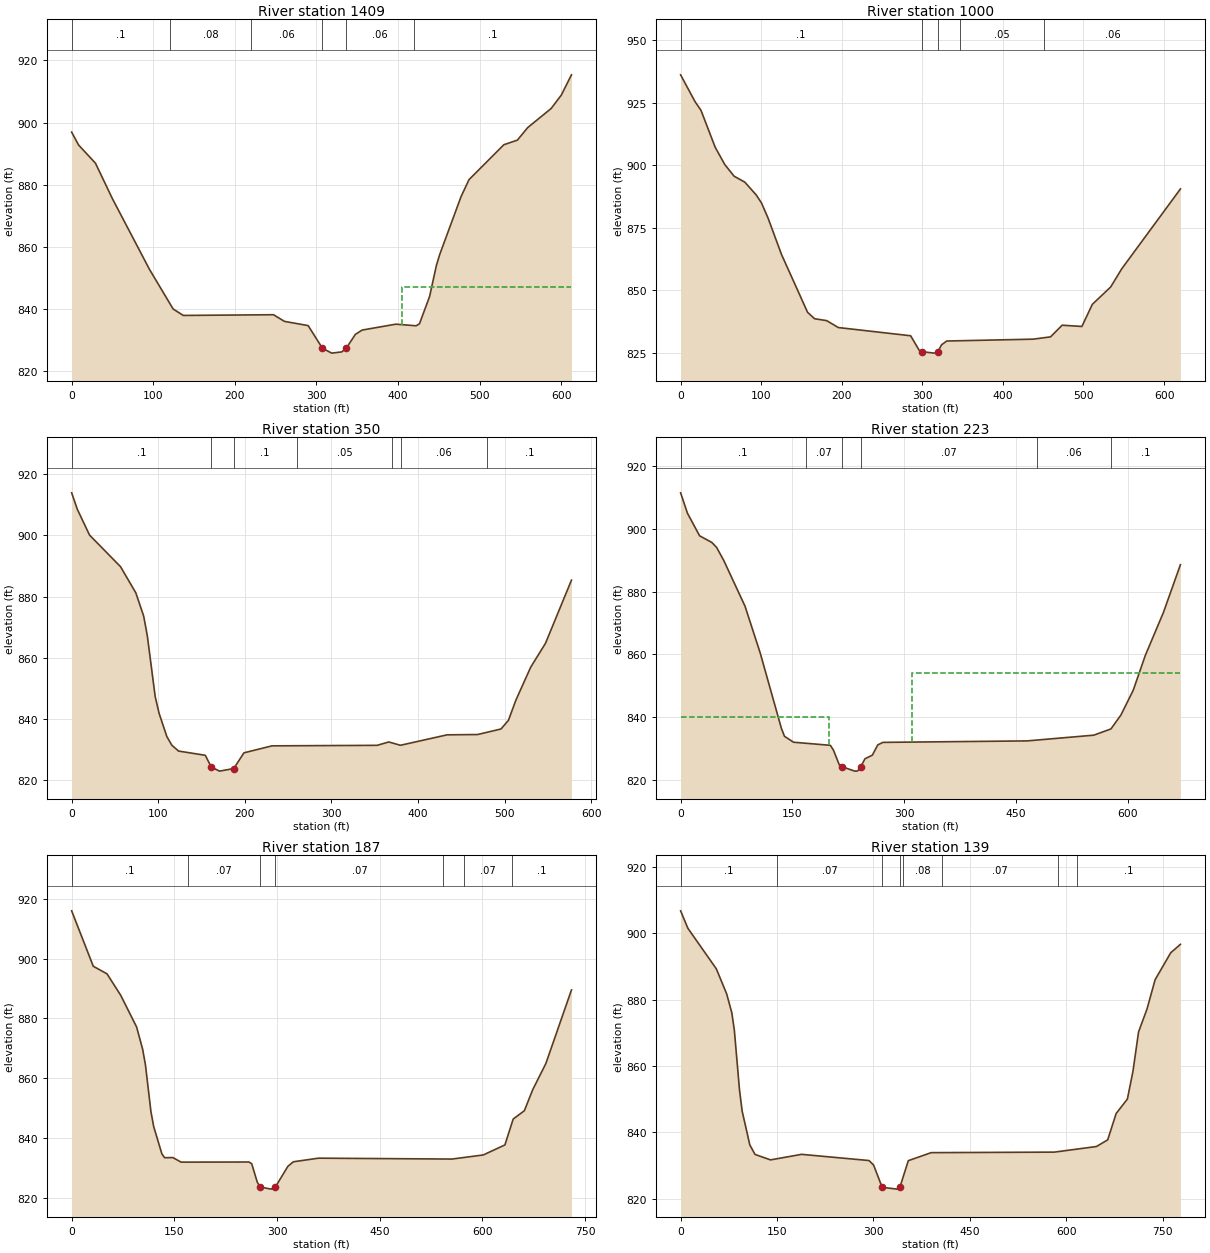
Type RM Length L Ch R = 1 ,1409    ,413.9,409.1,394.6
XS GIS Cut Line= 2
1669924.35709126 366165.312987971669332.04787777366321.878799179
#Sta/Elev= 30
       0  896.94     8.5  892.79    29.2  886.94    49.9  875.55    95.4  852.77
   124.4  840.02   136.8  837.94   247.4  838.17   260.9  836.03   289.9  834.67
   307.4827.3829   318.8  825.81   331.2  826.21   336.6827.3815   347.8  831.85
   356.1  833.23   397.4  835.13   422.3  834.61   426.4  835.27   438.8  844.05
   447.1  854.01   451.2  857.56   477.3  876.15   487.1  881.64   529.8  892.88
   546.4  894.36   559.1  898.41   587.8  904.55   600.2  908.84   612.7  915.38
#Mann= 6 ,-1,0
       0      .1       0     120     .08       0     220     .06       0
   307.4    .045       0   336.6     .06       0     420      .1       0
#XS Ineff= 2 , 0
                          404.99          847.08
Permanent Ineff=
       F       F
Bank Sta=307.4,336.6
XS Rating Curve= 0 ,0
Exp/Cntr(USF)=0,0
Exp/Cntr=0.3,0.1

Type RM Length L Ch R = 1 ,1000    ,649.7,649.8,647
XS GIS Cut Line= 6
1669556.79330017365662.8844580051669468.35810959365821.119705841
1669380.67783876365972.5695341681669345.58342075366038.913889676
1669311.91714951366120.1532285061669260.35130775366207.019524589
#Sta/Elev= 30
       0  936.08    17.9  925.36    25.3  921.89    42.9  907.14    54.7  900.27
    66.4  895.55    79.6   893.2    93.8  888.08   100.3   884.9   108.5  878.84
   125.2  864.28   157.6  841.13   166.3  838.58   181.3  837.82   195.7  835.06
   285.5  831.77   296.1  825.96   299.4825.4247   314.6  824.83   319.3  825.44
   323.9  828.17   330.3  829.67   437.4  830.41   459.1  831.33   473.5  835.99
     498  835.49     511  844.34   533.7  851.26   547.6   858.6   620.3  890.46
#Mann= 5 ,-1,0
       0      .1       0   299.4    .045       0   319.3      .1       0
  346.27     .05       0  451.33     .06       0
Bank Sta=299.4,319.3
XS Rating Curve= 0 ,0
Exp/Cntr(USF)=0,0
Exp/Cntr=0.3,0.1

Type RM Length L Ch R = 1 ,350     ,131.5,126.9,124.7
XS GIS Cut Line= 3
1669002.09268477365438.6323794121668782.66186896365866.355390927
1668748.13214668365956.578213668
#Sta/Elev= 30
       0  913.91     6.6   908.5    20.7  900.09    56.4  889.79    74.1  881.23
    83.1  873.71    86.1  869.23    87.6  866.76    96.5  847.29     101  841.85
     110  834.21   115.8  831.39   123.5  829.51   154.4  828.12   161.2824.3118
   170.8  822.95   187.2823.7985     199  828.93   231.4  831.21   352.8  831.38
   366.3  832.48   379.8   831.4   433.7  834.81   468.8  834.91   495.9  836.72
   504.5  839.56     513  846.08   530.2  856.91   547.3  864.73   577.3  885.37
#Mann= 7 ,-1,0
       0      .1       0   161.2    .045       0   187.2      .1       0
     260     .05       0     370     .07       0     380     .06       0
     480      .1       0
Bank Sta=161.2,187.2
XS Rating Curve= 0 ,0
Exp/Cntr(USF)=0,0
Exp/Cntr=0.3,0.1

Type RM Length L Ch R = 1 ,223     ,36.7,36.7,37
XS GIS Cut Line= 3
1668993.18035715365433.3374296151668828.16376481365463.896057827
1668738.01581158365958.945834859
#Sta/Elev= 30
       0  911.34     9.2  904.86    25.5  897.69    41.8   895.6    48.3  894.02
      58  889.83    86.5  875.32   106.9  860.44   135.3  836.54   139.4  834.02
   151.6  832.13     201  831.15   205.1  829.67   213.1  824.91   217.3   824.3
   233.8  822.95   237.6  822.98   241.7  824.29   247.5  826.88   257.4  828.02
   264.7  831.29   271.6  832.08   465.3  832.55   554.7  834.37   577.7  836.35
   591.1  840.76   607.6  848.62   623.8  859.66   648.2  873.36     671  888.52
#Mann= 6 ,-1,0
       0      .1       0  167.82     .07       0   217.3    .045       0
   241.7     .07       0  477.82     .06       0  577.82      .1       0
#XS Ineff= 2 , 0
          199.67  840.22     310          854.06
Permanent Ineff=
       F       F
Bank Sta=217.3,241.7
XS Rating Curve= 0 ,0
Exp/Cntr(USF)=0,0
Exp/Cntr=0.3,0.1

Type RM Length L Ch R = 1 ,187     ,43.9,47.4,50.1
XS GIS Cut Line= 3
1668991.65242574365407.362595635  1668799.133068 365419.58604692
1668704.40132055365948.250314985
#Sta/Elev= 30
       0  916.02    31.6  897.45    51.6  894.93    71.7  887.72    94.9  877.09
   103.7  869.65   107.8  864.39   115.8  848.77   119.8  843.78   131.8  834.62
   135.8  833.33   147.8  833.38   159.9  831.85   258.9  831.89     263  831.31
   271.1  825.15   275.1  823.53   291.4  822.81   297.6823.5388   315.8  830.44
   323.8  831.97   360.5  833.18   555.5  832.88   601.3  834.26   632.8  837.62
   644.9  846.29   661.2  849.07   673.4  856.11   692.6  864.88     730  889.52
#Mann= 7 ,-1,0
       0      .1       0     170     .07       0   275.1    .045       0
   297.6     .07       0  542.91     .06       0  572.91     .07       0
  642.91      .1       0
Bank Sta=275.1,297.6
XS Rating Curve= 0 ,0
Exp/Cntr(USF)=0,0
Exp/Cntr=0.3,0.1

Type RM Length L Ch R = 1 ,139     ,59.8,64.6,69.1
XS GIS Cut Line= 3
1668979.33134134365388.8377539211668793.87331682365370.793189373
1668556.28655027365912.130125821
#Sta/Elev= 30
       0  906.79    11.3  901.53    55.5  889.32    71.6  881.78    79.6   876.1
    83.6  870.78    91.6  852.79    95.7  846.42   107.7  836.17   115.8  833.32
   139.9  831.68   188.2  833.35   293.1  831.48   300.2  830.13   313.5  823.41
   336.8  822.86   341.1  823.44   354.2  831.44   389.8  833.86   581.4  834.02
   646.9  835.71   664.4  837.73   677.5  845.66     695  850.02   703.7  858.43
   712.4  870.28   725.5  877.17   738.1     886   762.4  894.14   777.5  896.69
#Mann= 8 ,-1,0
       0      .1       0     150     .07       0   313.5    .045       0
   341.1     .07       0  346.33     .08       0  406.33     .07       0
  586.33     .08       0  616.33      .1       0
Bank Sta=313.5,341.1
XS Rating Curve= 0 ,0
Exp/Cntr(USF)=0,0
Exp/Cntr=0.3,0.1

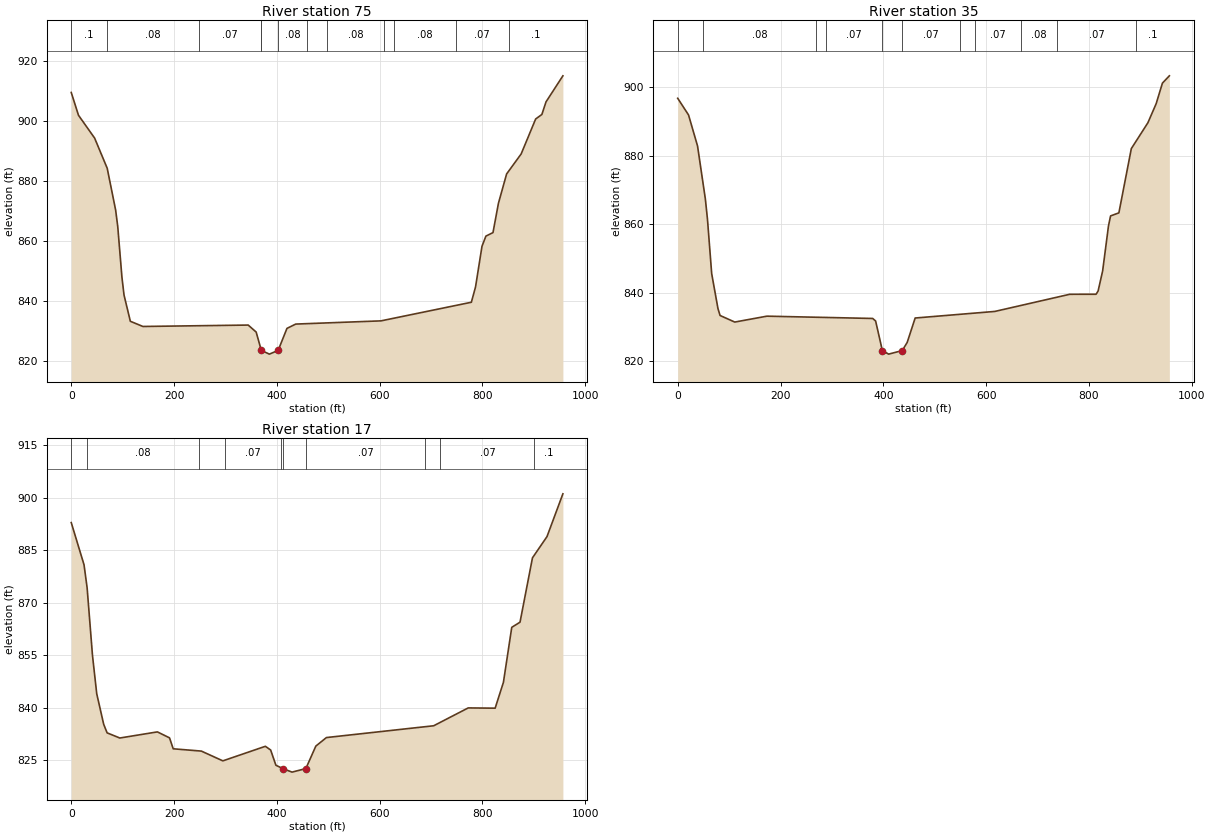
Type RM Length L Ch R = 1 ,75      ,40.1,40,42.4
XS GIS Cut Line= 4
1668988.59656292365376.8039674231668794.54927377365335.549819337
 1668438.5412551365771.0102713561668464.51608908365965.057560501
#Sta/Elev= 30
       0  909.57    14.1  901.97    45.5  894.37      70  884.31    86.4  870.37
    90.5  864.88    98.6  848.07   102.7  842.08     115  833.35   139.5  831.62
   344.3  832.09   359.8  829.76   369.8823.6559   385.5  822.41   402.6  823.65
   419.7  830.98   436.8  832.42   602.7  833.49   778.5  839.69   786.6  844.76
   799.2  858.34   806.8  861.72   820.6  862.89   831.2  872.66   847.1  882.42
   875.4  889.09   903.6  900.73   915.7  902.24   923.8  906.44   956.6  915.11
#Mann= 12 ,-1,0
       0      .1       0      70     .08       0  248.38     .07       0
  368.38     .08       0   369.8    .045       0   402.6     .08       0
  458.38     .07       0  498.38     .08       0  608.38     .07       0
  628.38     .08       0  748.38     .07       0  850.85      .1       0
Bank Sta=369.8,402.6
XS Rating Curve= 0 ,0
Exp/Cntr(USF)=0,0
Exp/Cntr=0.3,0.1

Type RM Length L Ch R = 1 ,35      ,20.9,17.5,25.2
XS GIS Cut Line= 4
1668968.73345458 365341.661544981668774.68616543365300.407396894
1668418.67814677365735.8678489131668444.65298075365929.915138058
#Sta/Elev= 30
       0  896.71    21.1  891.84    38.6  882.79    53.8  867.33    57.9  861.45
    66.1  845.58    78.3   835.4    82.4  833.37     111  831.45   173.5  833.17
   379.4   832.5   385.1  831.75   398.2 823.121   410.4   822.1   436.8823.1328
   446.5  825.51     462  832.63     617  834.55   762.7  839.55     814  839.56
     818  840.52   826.8  846.37   838.2  859.54   842.2   862.4   858.4   863.3
   882.6  882.03   914.9  889.59     931  895.16   943.1  901.13   956.6  903.26
#Mann= 11 ,-1,0
       0      .1       0      50     .08       0  268.38      .1       0
  288.38     .07       0   398.2    .045       0   436.8     .07       0
  548.38     .08       0  578.38     .07       0  668.38     .08       0
  738.38     .07       0  890.85      .1       0
Bank Sta=398.2,436.8
XS Rating Curve= 0 ,0
Exp/Cntr(USF)=0,0
Exp/Cntr=0.3,0.1

Type RM Length L Ch R = 1 ,17      ,,,
XS GIS Cut Line= 4
 1668956.5100033365330.9660251061668762.46271415 365289.71187702
1668406.45469548365725.1723290381668432.42952946365919.219618184
#Sta/Elev= 30
       0  892.92    24.9  880.85    30.9  874.27    41.3  854.99    49.6     844
    63.1  835.28    69.8  832.82    94.5  831.35   167.6   833.1   191.2   831.4
   198.4  828.27   253.2  827.61     295  824.82   377.7  828.98     388  827.92
   398.2  823.57   411.8822.6146   429.6   821.6   456.5822.6182   475.9  829.04
   496.5  831.48   705.2  834.85   772.4  839.95   824.8  839.88   840.9  847.27
   857.1  862.98   873.2  864.46   897.4  882.84   925.7  888.92   956.6  901.14
#Mann= 10 ,-1,0
       0      .1       0      30     .08       0  248.38      .1       0
  298.38     .07       0  408.38      .1       0   411.8    .045       0
   456.5     .07       0  688.38     .08       0  718.38     .07       0
  900.85      .1       0
Bank Sta=411.8,456.5
XS Rating Curve= 0 ,0
Exp/Cntr(USF)=0,0
Exp/Cntr=0.3,0.1
LCMann Table=0

Chan Stop Cuts=-1
Use User Specified Reach Order=0
Composite Channel Slope=5